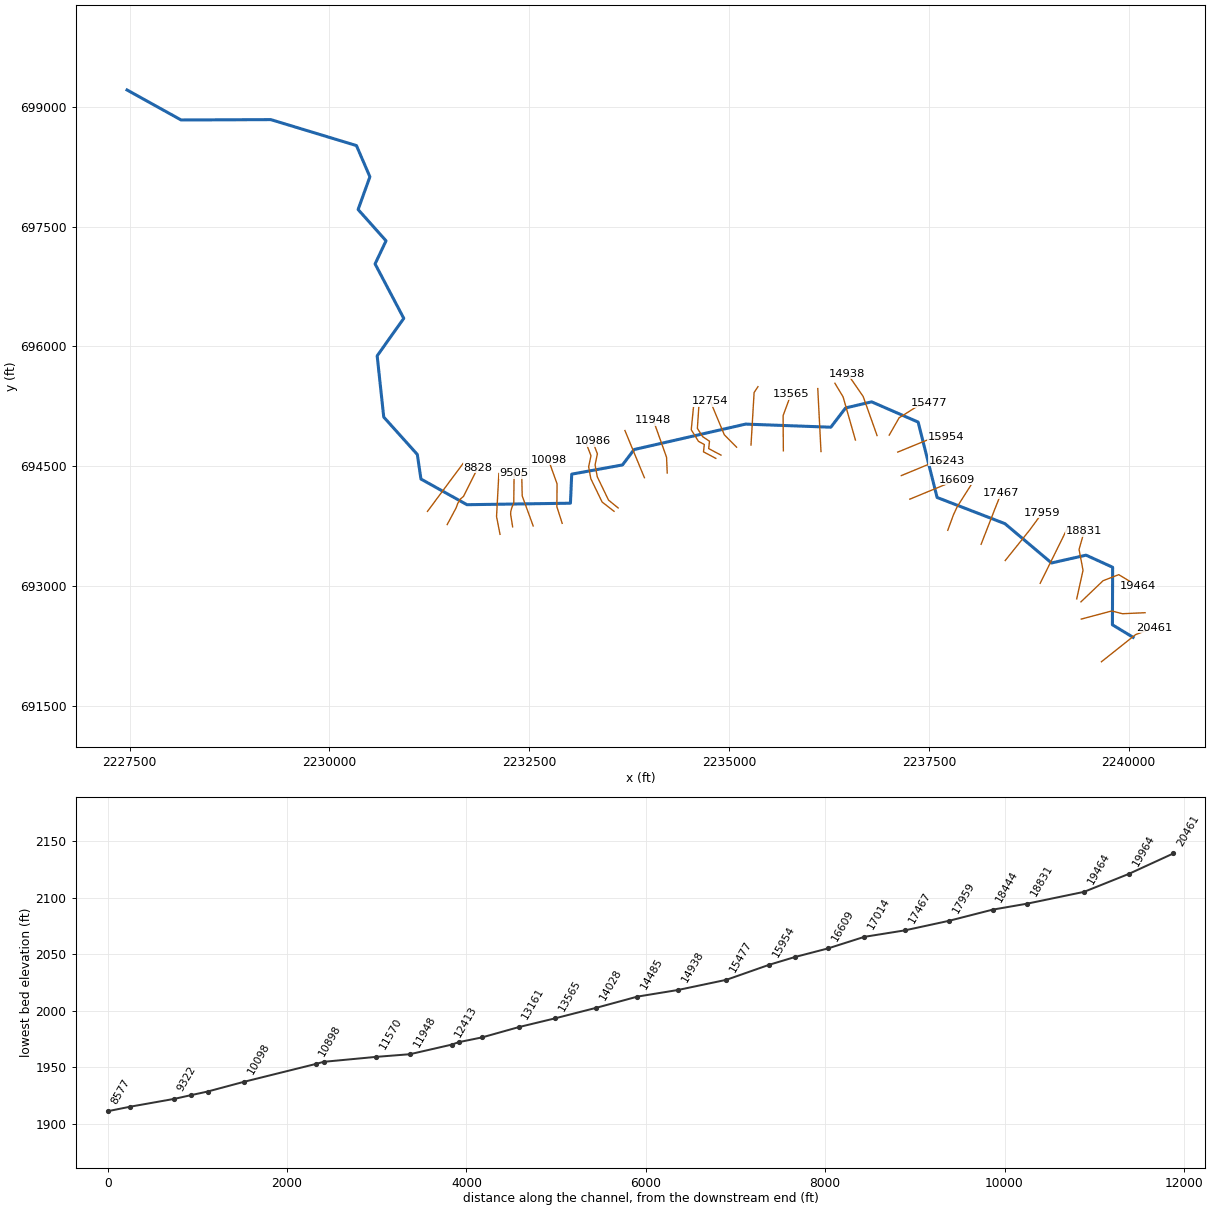
--- LAURELCK.prj (project) ---

Proj Title=LAURELCK
Current Plan=p01
Default Exp/Contr=0,0
English Units
Geom File=g01
Flow File=f01
Plan File=p01
BEGIN DESCRIPTION:
----------MODEL BY WSP USA 2022----------
AFH study
Randolph County, WV
HEC-RAS Version: RAS 6.2
Vertical Datum: NAVD88
Projection: NAD 1983 StatePlane West Virginia S FIPS 4702 (US Feet)
Terrain: 1-meter LIDAR (FEMA Region III 3DEP collected 2016-2018)
Land Use: 2019 NLCD
Hydrologic Method:
WV SIR2010-5033 regression equations
Additional Model Notes:
None
END DESCRIPTION:
DSS Export Rating Curves= 0
DSS Export Rating Curve Sorted= 0
DSS Export Volume Flow Curves= 0
DXF OffsetX= 0
DXF OffsetY= 0
DXF ScaleX= 0
DXF ScaleY= 0

--- LAURELCK.p01 (plan) ---

Plan Title=Floodplain
Program Version=6.20
Short Identifier=Floodplain
Geom File=g01
Flow File=f01
Subcritical Flow
K Sum by GR= 0
Std Step Tol= 0.01
Critical Tol= 0.01
Num of Std Step Trials= 20
Max Error Tol= 0.3
Flow Tol Ratio= 0.001
Split Flow NTrial= 30
Split Flow Tol= 0.02
Split Flow Ratio= 0.02
Log Output Level= 0
Friction Slope Method= 1
Unsteady Friction Slope Method= 2
Unsteady Bridges Friction Slope Method= 1
Parabolic Critical Depth
Global Vel Dist= 0 , 0 , 0
Global Log Level= 0
CheckData=True
Encroach Param=-1 ,0,0, 0
Mapping Interval=1HOUR
Computation Time Step Use Courant=        0
Computation Time Step Use Time Series=    0
Computation Time Step Count To Double=0
Computation Time Step Max Doubling=0
Computation Time Step Max Halving=0
Computation Time Step Residence Courant=0
Run HTab= 0
Run UNet= 0
Run Sediment= 0
Run PostProcess= 0
Run WQNet= 0
Run RASMapper=-1
UNET Theta= 0
UNET Theta Warmup= 0
UNET ZTol= 0
UNET ZSATol= 0
UNET MxIter= 0
UNET Max Iter WO Improvement= 0
UNET MaxInSteps= 0
UNET DtIC= 0
UNET DtMin= 0
UNET MaxCRTS= 0
UNET WFStab= 0
UNET SFStab= 0
UNET WFX= 1
UNET SFX= 1
UNET Gravity=32.174
UNET 1D Methodology=Finite Difference
UNET DSS MLevel= 1
UNET Pardiso=0
UNET DZMax Abort= 0
UNET Use Existing IB Tables= 0
UNET Froude Reduction=False
UNET Froude Limit= 0
UNET Froude Power= 0
UNET D1 Cores= 0
UNET WindReference=Eulerian
UNET WindDragFormulation=Hsu (1988)
UNET D2 Coriolis=0
UNET D2 Cores= 0
UNET D2 Theta= 1
UNET D2 Theta Warmup= 1
UNET D2 Z Tol= 0.01
UNET D2 Volume Tol= 0.01
UNET D2 Max Iterations= 20
UNET D2 Equation= 0
UNET D2 RampUpFraction=0.1
UNET D2 TimeSlices= 1
UNET D2 Turbulence Formulation=Non-Conservative (original)
UNET D2 Eddy Viscosity=0.3
UNET D2 Transverse Eddy Viscosity=0.1
UNET D2 Smagorinsky Mixing=0
UNET D2 BCVolumeCheck=0
UNET D2 Cores=0
UNET D2 SolverType=PARDISO (Direct)
UNET D2 Minimum Iterations= 2147483647
UNET D2 Maximum Iterations= 2147483647
UNET D2 Restart Number= 10
UNET D2 Relaxation Coeff=1.3
UNET D2 SOR Precondition Iterations= 10
UNET D2 ILUT Maximum Fill= 8
UNET D2 ILUT Tolerance=1E-08
UNET D1D2 MaxIter= 0
UNET D1D2 ZTol=0.01
UNET D1D2 QTol=0.1
UNET D1D2 MinQTol=1
Write IC File= 0
Write IC File at Fixed DateTime=0
Write IC File at Sim End=0
Echo Input=False
Echo Parameters=False
Echo Output=False
Write Detailed= 0
HDF Write Warmup=0
HDF Write Time Slices=0
HDF Flush=0
HDF Compression= 1
HDF Chunk Size= 1
HDF Spatial Parts= 1
HDF Use Max Rows=0
HDF Fixed Rows= 1
Calibration Method= 0
Calibration Iterations= 20
Calibration Max Change=0.05
Calibration Tolerance=0.2
Calibration Maximum=1.5
Calibration Minimum=0.5
Calibration Optimization Method= 1
WQ AD Non Conservative
WQ ULTIMATE=-1
WQ Max Comp Step=1HOUR
WQ Output Interval=15MIN
WQ Output Selected Increments= 0
WQ Output face flow=0
WQ Output face velocity=0
WQ Output face area=0
WQ Output face dispersion=0
WQ Output cell volume=0
WQ Output cell surface area=0
WQ Output cell continuity=0
WQ Output cumulative cell continuity=0
WQ Output face conc=0
WQ Output face dconc_dx=0
WQ Output face courant=0
WQ Output face peclet=0
WQ Output face adv mass=0
WQ Output face disp mass=0
WQ Output cell mass=0
WQ Output cell source sink temp=0
WQ Output nsm pathways=0
WQ Output nsm derived pathways=0
WQ Create Restart=0
WQ Fixed Restart=0
WQ System Summary=0
WQ Write To DSS=0
Sorting and Armoring Iterations= 10
XS Update Threshold= 0.02
Bed Roughness Predictor= 0
Hydraulics Update Threshold= 0.02
Energy Slope Method= 1
Volume Change Method= 1
Sediment Retention Method= 0
Sediment TS Multiplier= 1
Warm Up Method= 0
XS Weighting Method= 0
Number of US Weighted Cross Sections= 1
Number of DS Weighted Cross Sections= 1
Upstream XS Weight=0
Main XS Weight=1
Downstream XS Weight=0
Number of DS XS's Weighted with US Boundary= 1
Upstream Boundary Weight= 1
Weight of XSs Associated with US Boundary= 0
Number of US XS's Weighted with DS Boundary= 1
Downstream Boundary Weight= 0.5
Weight of XSs Associated with DS Boundary= 0.5
Percentile Method= 0
Sediment Output Level= 3
Mass or Volume Output= 0
Output Increment Type= 1
Profile and TS Output Increment= 1
Transport Output Increment 1
XS Output Flag= 0
XS Output Increment= 10
Read HDF5 Sediment Hotstart= 0
Sediment Hotstart Type= 0
Write Gradation File= 0
Read Gradation Hotstart= 0
Write HDF5 File= 1
Write Binary Output= 1
Write DSS Sediment File= 0
DSS Sediment Output Type= 1
SV Curve= 0
Specific Gage Flag= 0
Subcell Erosion Methods= 0
Subcell Deposition Methods= 0
Advection Scheme= 1
Matrix Solver= 0
Implicit Weighting Factor= 1
Maximum Outer Loop Convergence Iterations= 5
Convergence Maximum Absolute= 0.001
Convergence RMSE= 0.0001
Grain Fractions Max Abs Error= 0.001
Max Subgrid Regions= 1
Max Subgrid Length Scale= 3.402823E+38
Initial Layer Thickness= 3.402823E+38
Min Layer Thickness= 3.402823E+38
Max Layer Thickness= 3.402823E+38
Number of Layers= 5

--- LAURELCK.f01 (steady flow) ---

Flow Title=Flow
Program Version=4.00
Number of Profiles=1
Profile Names=P100yr
River Rch & RM=LAURELCK,Main,20461
     558
River Rch & RM=LAURELCK,Main,17959
     622
River Rch & RM=LAURELCK,Main,14938
     692
River Rch & RM=LAURELCK,Main,11948
     869
River Rch & RM=LAURELCK,Main,10986
     968
River Rch & RM=LAURELCK,Main,7927
    1090
River Rch & RM=LAURELCK,Main,4217
    1620
Boundary for River Rch & Prof#=LAURELCK,Main      ,1
Up Type=0
Dn Type=3
Dn Slope=0.009369

--- LAURELCK.g01 (geometry) ---

Geom Title=Geometry
Program Version=6.20

River Reach=LAURELCK        ,Main
Reach XY= 30
     2240055.197      692355.541     2239796.235      692512.308
      2239799.07      693233.105     2239466.895      693384.621
     2239034.364      693287.081     2238451.774      693779.213
     2237602.671      694107.541     2237365.586      695051.852
      2236783.64       695305.68     2236458.004      695229.135
      2236272.97      694987.813     2235206.773      695026.596
     2233811.815      694707.943     2233666.363      694515.063
     2233031.267      694399.435      2233015.02      694035.664
     2231720.853      694016.858     2231144.948      694338.319
     2231099.381      694646.339     2230679.408      695114.642
     2230597.078      695882.068     2230929.885      696351.599
     2230570.987      697033.765     2230708.027      697322.957
      2230358.52      697715.131     2230506.001      698124.796
     2230337.819      698516.208     2229266.549       698841.28
     2228144.544      698836.799     2227467.297       699212.82

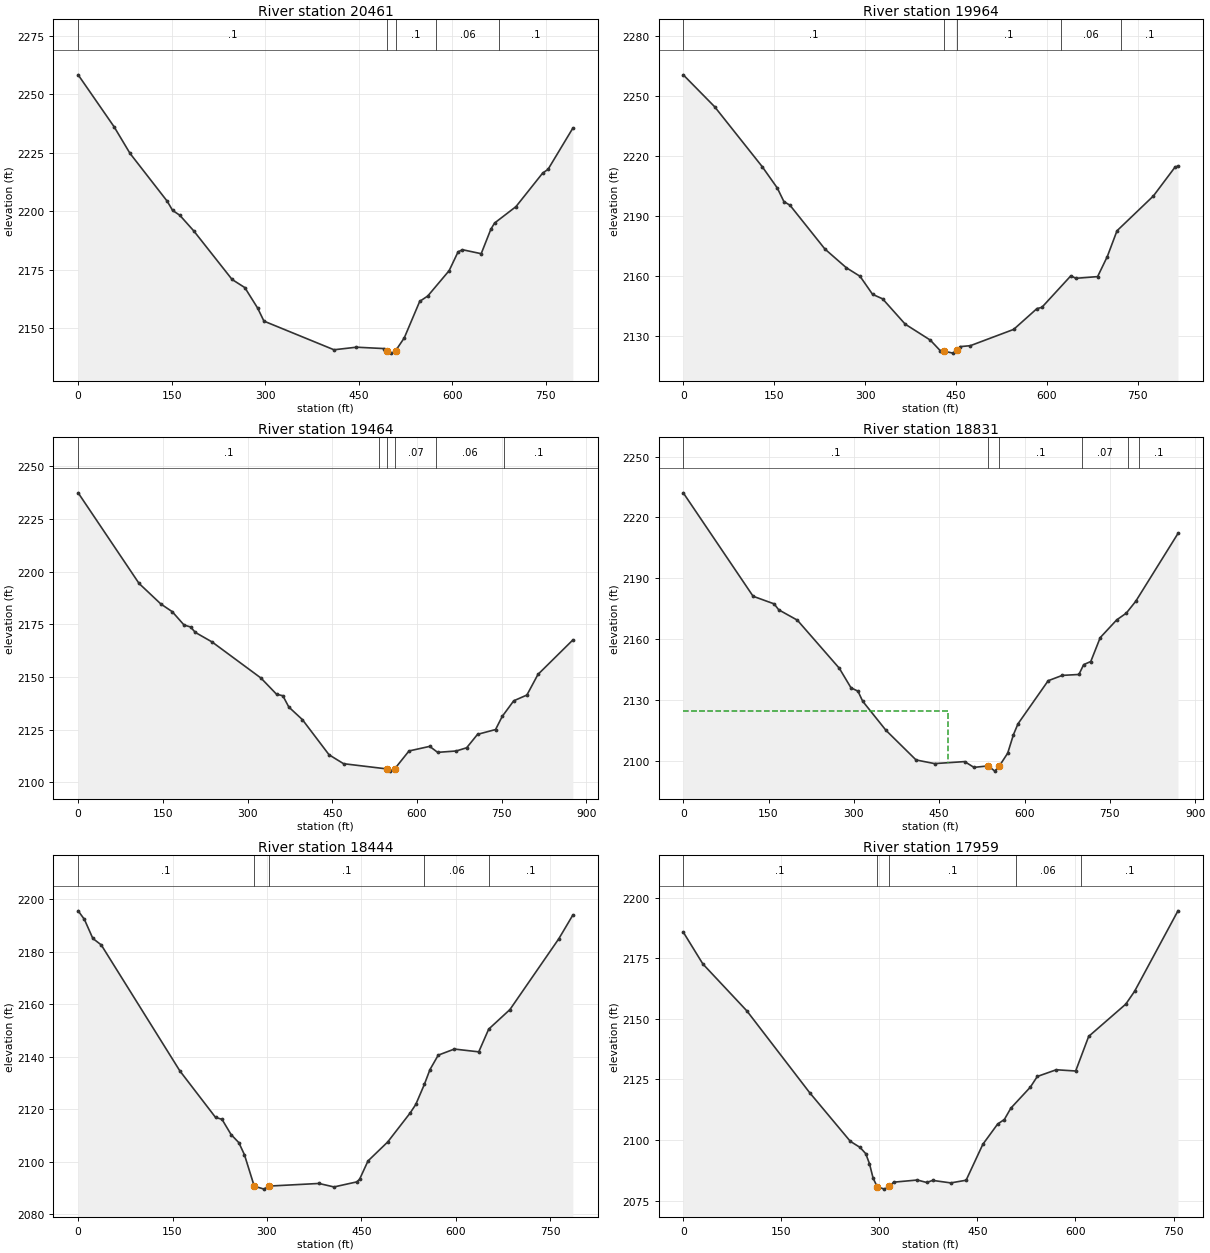
Type RM Length L Ch R = 1 ,20461   ,505.6,497.5,485.7
XS GIS Cut Line= 3
2239659.06802255 692049.441842132240084.83559405692388.488706812
2240317.30407487692478.100045106
#Sta/Elev= 30
       0 2258.25    57.7 2236.05    83.2  2224.7   142.9 2204.26   151.5 2200.35
   162.9 2198.33   185.5 2191.59   246.9 2170.87   267.3 2167.41   287.8 2158.69
     298 2153.09   410.3 2140.86   446.3 2141.96   490.2 2141.38   495.9 2140.39
   502.5 2139.43  509.012140.409     523 2145.93   547.8 2161.53   560.7 2163.82
     595 2174.65   609.3 2182.66   616.4 2183.58   646.4 2181.88   661.9 2192.35
   667.9 2194.98   702.2 2201.99     745 2216.31   753.6  2217.9   793.4  2235.5
#Mann= 5 ,-1,0
       0      .1       0   495.9    .045       0  509.01      .1       0
  574.27     .06       0  674.27      .1       0
Bank Sta=495.9,509.01
XS Rating Curve= 0 ,0
Exp/Cntr=0.3,0.1

Type RM Length L Ch R = 1 ,19964   ,491.9,499.3,502.4
XS GIS Cut Line= 4
2239406.23725575692583.8078344582239788.30946729692685.688650667
2239921.11655079692651.0912711322240204.66796978692663.708921186
#Sta/Elev= 30
       0 2260.42    51.7  2244.5   130.3 2214.51   155.2 2203.84   166.1 2197.05
   176.1 2195.23   233.8 2173.32   269.2 2163.96   291.8 2159.69   312.5 2150.66
     329 2148.43   366.3 2135.77   407.7  2127.8   424.2 2122.49   430.72122.253
   444.9 2121.28   451.72122.627   457.3 2124.54   473.8    2125   545.3 2133.14
   583.8 2143.56   591.8 2144.14   639.8 2159.97   647.8 2158.68   683.9 2159.54
   699.9 2169.59   715.9 2182.46     776 2199.88     812 2214.42   816.5 2214.74
#Mann= 5 ,-1,0
       0      .1       0   430.7    .045       0   451.7      .1       0
  622.66     .06       0  722.66      .1       0
Bank Sta=430.7,451.7
XS Rating Curve= 0 ,0
Exp/Cntr=0.3,0.1

Type RM Length L Ch R = 1 ,19464   ,616.1,632.9,640.3
XS GIS Cut Line= 4
2239402.30805278  692799.50761662239679.38210507693064.654288518
2239875.66052639693140.4518872352240117.08155615692994.277585916
#Sta/Elev= 30
       0 2237.34   107.8 2194.39   146.5 2184.62   166.6 2180.99   187.6 2174.64
   199.1 2173.73   207.4 2171.17   237.3  2166.6   323.7 2149.52   351.4 2141.82
   362.5 2141.12   373.1 2135.76   397.2 2129.77   444.4  2113.1   470.1 2108.89
   547.3  2106.4   551.6 2105.37  560.582106.447   585.9 2114.93   622.6 2117.11
   636.6 2114.27   669.5 2114.92     688 2116.44   707.3 2122.81   739.2 2125.09
     751 2131.31   771.4 2138.72   794.7 2141.45   814.3 2151.23   876.1 2167.57
#Mann= 6 ,-1,0
       0      .1       0   533.5     .06       0   547.3    .045       0
  560.58     .07       0  633.91     .06       0  753.91      .1       0
Bank Sta=547.3,560.58
XS Rating Curve= 0 ,0
Exp/Cntr=0.3,0.1

Type RM Length L Ch R = 1 ,18831   ,395.2,387.5,380.4
XS GIS Cut Line= 4
2239349.43346036692837.2695594052239428.58667577693195.024910954
2239378.86748719693455.663767468 2239443.7702625693684.692423274
#Sta/Elev= 30
       0 2232.16   122.8 2181.16   159.7 2177.41   167.9 2174.47   200.6 2169.37
   274.4 2145.64   294.9 2136.03   307.2 2134.34   315.4 2129.43   356.3 2115.08
   409.3 2100.44   441.9 2098.64   494.8 2099.63   511.1 2096.78  536.162097.513
   547.8 2094.93   555.9 2097.54   570.4 2103.78   580.6 2112.96   588.5 2118.25
   641.6 2139.51   666.4 2142.14   695.6 2142.59     704 2147.44   716.5 2148.98
   733.1 2160.76   762.2 2169.54   778.8  2172.8   795.5 2178.65   869.8 2212.12
#Mann= 6 ,-1,0
       0      .1       0  536.16    .045       0   555.9      .1       0
  701.75     .07       0  781.75     .06       0  801.75      .1       0
#XS Ineff= 2 , 0
           465.7 2124.69
Permanent Ineff=
       F       F
Bank Sta=536.16,555.9
XS Rating Curve= 0 ,0
Exp/Cntr=0.3,0.1

Type RM Length L Ch R = 1 ,18444   ,487,485.2,482.3
XS GIS Cut Line= 3
2238892.48220298693032.3173093432239137.75212125693528.550955354
2239240.26750988693737.192693096
#Sta/Elev= 30
       0 2195.61     9.9 2192.36    23.3  2185.1    36.7 2182.62   161.6 2134.63
   218.4 2116.88   228.5  2116.2     243 2110.37   255.3  2107.3   264.2  2102.7
  279.752090.736   295.4 2089.59   302.5 2090.74   382.6 2091.75   406.5 2090.42
   442.7 2092.35   447.2 2093.37   460.5 2100.32   491.8 2107.55   527.5  2118.6
   536.4 2121.84     550 2129.45     559 2135.15   572.1 2140.63   597.7 2142.95
   636.5 2141.89   652.3 2150.55     686 2157.99   763.7 2184.98     786 2194.01
#Mann= 5 ,-1,0
       0      .1       0  279.75    .045       0   302.5      .1       0
     550     .06       0  653.54      .1       0
Bank Sta=279.75,302.5
XS Rating Curve= 0 ,0
Exp/Cntr=0.3,0.1

Type RM Length L Ch R = 1 ,17959   ,487.8,491.5,494.4
XS GIS Cut Line= 3
2238455.34166333 693317.732138572238760.66435887693698.793732617
2238919.39632179693915.410507441
#Sta/Elev= 30
       0 2185.79      30 2172.64    97.3 2153.28   193.2 2119.58   255.6 2099.44
   270.5 2096.93   279.1 2094.38   284.8 2090.28   290.4 2084.27   296.6 2080.76
   307.5 2079.72   315.42080.841   321.8 2082.59   358.1 2083.48   372.4 2082.46
   381.5 2083.32   409.3 2082.29   432.7 2083.39   458.3 2098.23     481  2106.6
   491.2 2108.45   501.1 2113.12   530.9 2121.79   541.6 2126.21   570.6 2128.98
   600.3 2128.47   620.2 2142.75     677 2156.08   690.5 2161.39   756.8 2194.57
#Mann= 5 ,-1,0
       0      .1       0   296.6    .045       0   315.4      .1       0
  508.29     .06       0  608.29      .1       0
Bank Sta=296.6,315.4
XS Rating Curve= 0 ,0
Exp/Cntr=0.3,0.1

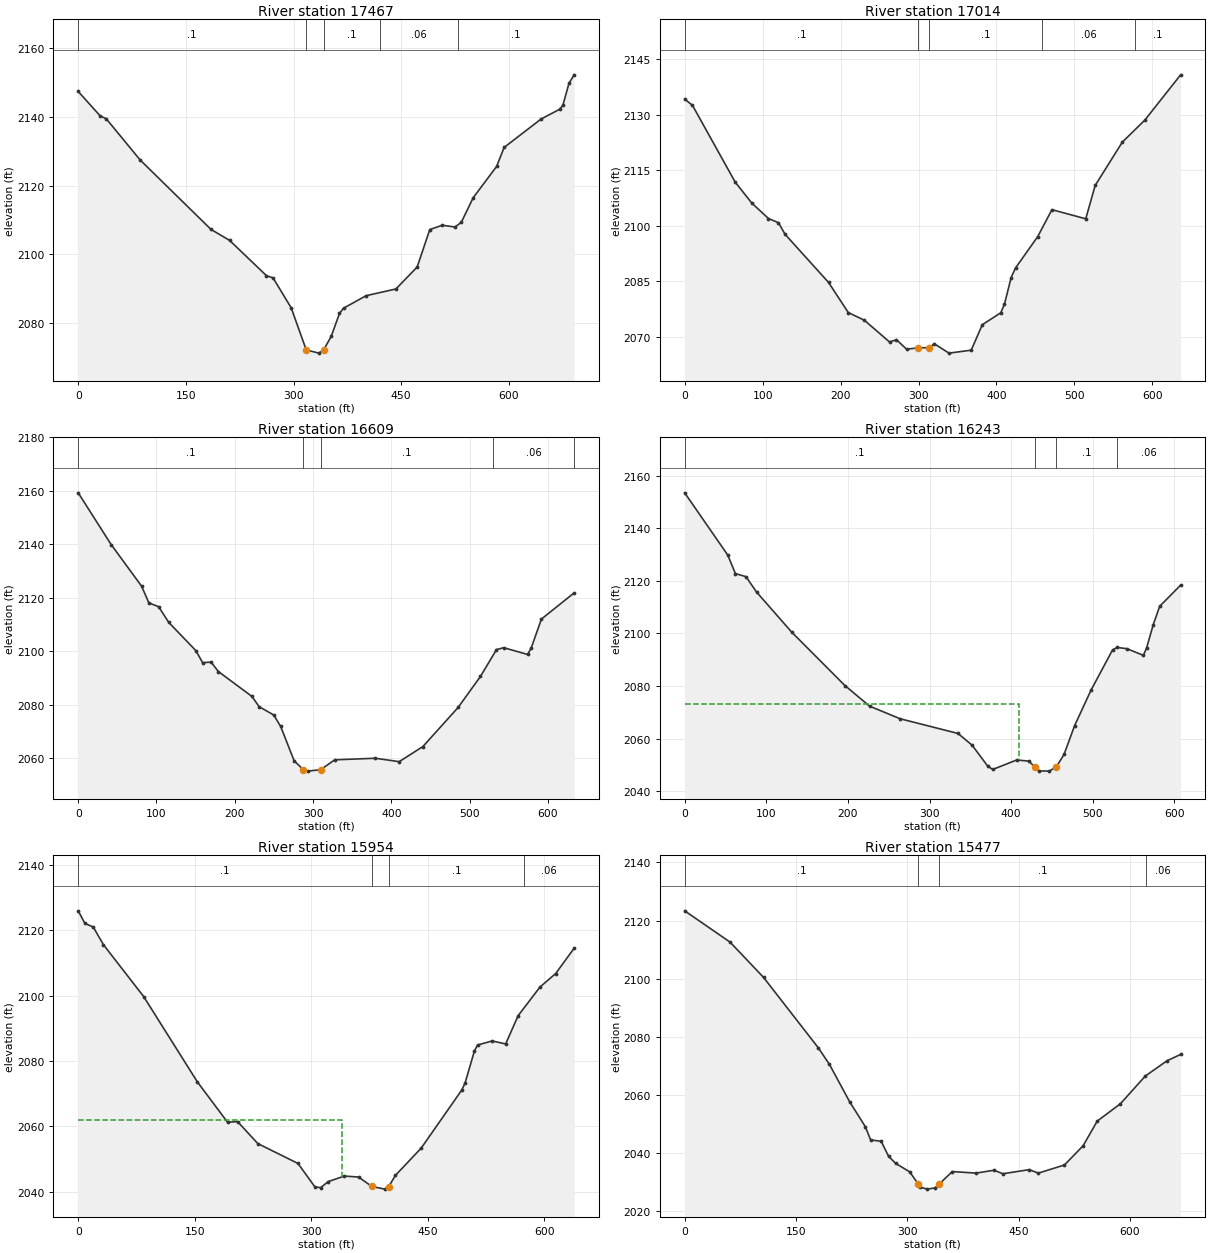
Type RM Length L Ch R = 1 ,17467   ,453,453,452.7
XS GIS Cut Line= 3
2238153.30005196693520.7436979752238327.15728958693967.289834105
2238405.86152476 694163.85511637
#Sta/Elev= 30
       0 2147.37    30.5 2140.29    39.1 2139.42    86.3 2127.44     185 2107.24
   210.8 2104.07   262.3 2093.78   271.4 2093.15   296.6 2084.48   317.7 2072.19
   335.3 2071.26  341.772072.157   352.5 2076.14     364 2082.83   369.6 2084.32
   401.1 2087.97   442.6 2089.92   472.2 2096.31   489.8  2107.2   507.1 2108.46
     525 2107.95   533.7 2109.31   550.2 2116.44     583  2125.6   593.3 2131.08
     645 2139.38   670.8  2142.2   675.3 2143.41   683.7 2149.75   690.9 2152.21
#Mann= 5 ,-1,0
       0      .1       0   317.7    .045       0  341.77      .1       0
     420     .06       0   529.2      .1       0
Bank Sta=317.7,341.77
XS Rating Curve= 0 ,0
Exp/Cntr=0.3,0.1

Type RM Length L Ch R = 1 ,17014   ,413.6,405.4,398.2
XS GIS Cut Line= 4
2237736.20993072693696.2559992282237807.17223762693889.789563511
2237854.22541632693991.5127534312238024.70019625694259.930679627
#Sta/Elev= 30
       0  2134.2      10  2132.5    64.9 2111.72    86.2 2106.06   107.5 2101.91
   120.3 2100.78   128.8 2097.64   184.6 2084.62   209.9 2076.47   230.5 2074.41
   262.8 2068.52   271.6 2069.14   284.8 2066.56   299.8 2066.97   313.3 2066.96
   320.2 2068.04   339.1 2065.51   367.6 2066.31   381.8  2073.2   405.5 2076.42
   410.2 2078.73   418.8 2085.94   424.4 2088.53   452.9 2097.02   471.1  2104.3
   514.5 2101.83   526.6 2110.85   561.4 2122.56   590.3 2128.52   636.2 2140.76
#Mann= 5 ,-1,0
       0      .1       0   299.8    .045       0   313.3      .1       0
  458.21     .06       0  578.21      .1       0
Bank Sta=299.8,313.3
XS Rating Curve= 0 ,0
Exp/Cntr(USF)=0,0
Exp/Cntr=0.3,0.1

Type RM Length L Ch R = 1 ,16609   ,364.8,365.8,367.2
XS GIS Cut Line= 2
2237261.28773799694086.2606310922237846.72676995694328.177586446
#Sta/Elev= 30
       0 2159.25    42.1 2139.91      81 2124.35    90.2 2118.14   102.7 2116.69
   115.7 2110.81   150.3 2100.28   158.9 2095.78   169.8 2095.99     179 2092.47
   221.9 2083.17   231.1 2079.34   249.8 2076.22   258.6 2071.96   275.8 2059.13
   287.6 2055.78   293.1 2055.25   309.72055.798   327.7 2059.48   379.7 2060.06
     410 2058.78   440.3 2064.44   485.3 2079.05   513.8 2090.63   534.3 2100.66
   543.5 2101.38   574.1 2098.84   578.8 2101.39   591.7 2112.08   633.5 2121.86
#Mann= 5 ,-1,0
       0      .1       0   287.6    .045       0   309.7      .1       0
     530     .06       0  633.45      .1       0
Bank Sta=287.6,309.7
XS Rating Curve= 0 ,0
Exp/Cntr(USF)=0,0
Exp/Cntr=0.3,0.1

Type RM Length L Ch R = 1 ,16243   ,288.6,288.5,288.2
XS GIS Cut Line= 3
2237154.84427764694381.3993166242237598.35869579694565.256202693
2237725.76829227  694570.0945418
#Sta/Elev= 30
       0 2153.43    52.9 2129.72    62.1 2122.75    75.1 2121.57      88 2115.76
   131.3 2100.44   196.3 2080.22   226.6 2072.36   264.1 2067.58   334.9    2062
   352.2 2057.53   371.2 2049.61   377.4 2048.32   406.8 2051.93   421.5 2051.49
   429.4 2049.18   434.4 2047.78   446.6 2047.69   455.2 2049.23   464.8 2054.04
   477.7 2064.95   497.9  2078.5   524.2 2093.73     530 2094.69     542 2094.19
     562 2091.67     566 2094.58     574 2103.26   581.9 2110.29   607.6 2118.36
#Mann= 4 ,-1,0
       0      .1       0   429.4    .045       0   455.2      .1       0
  530.11     .06       0
#XS Ineff= 2 , 0
          409.89  2073.1
Permanent Ineff=
       F       F
Bank Sta=429.4,455.2
XS Rating Curve= 0 ,0
Exp/Cntr(USF)=0,0
Exp/Cntr=0.3,0.1

Type RM Length L Ch R = 1 ,15954   ,473.4,477.4,475.9
XS GIS Cut Line= 3
2237110.22083167694675.8916460112237503.01059405694836.996695535
2237715.78223274694861.036302025
#Sta/Elev= 30
       0 2125.97     8.6 2122.12    19.4    2121    32.4 2115.63    84.3 2099.73
   153.4 2073.63   192.3 2061.27   205.3 2061.45   231.3 2054.73   283.1 2048.64
   304.7 2041.51   312.1 2041.22     322  2043.1   342.8 2044.79     361 2044.49
   378.2  2041.6   394.9 2040.79   399.9 2041.56   408.5 2044.99   441.8 2053.37
   494.1 2071.16   498.3 2073.34   510.3  2083.1   514.3  2084.9   533.1 2086.14
   550.5 2085.23   566.6  2093.9   594.8 2102.67   614.9 2106.77   638.7 2114.53
#Mann= 4 ,-1,0
       0      .1       0   378.2    .045       0   399.9      .1       0
  574.55     .06       0
#XS Ineff= 2 , 0
          339.64  2061.9
Permanent Ineff=
       F       F
Bank Sta=378.2,399.9
XS Rating Curve= 0 ,0
Exp/Cntr=0.3,0.1

Type RM Length L Ch R = 1 ,15477   ,520.2,538.8,552.6
XS GIS Cut Line= 4
2237003.40425494694888.0037845812237127.63649012695105.488219078
2237348.10479188695245.6314364112237497.54481435695292.824299585
#Sta/Elev= 30
       0 2123.34    61.2 2112.56   106.4 2100.38   180.3 2076.08   195.1 2070.44
   222.5 2057.49   243.5 2048.97   250.6 2044.43   264.8 2043.94   274.8 2038.79
   284.3 2036.34   303.2 2033.44   314.4 2029.37   317.5 2028.17   326.9 2027.47
   337.6 2027.91   343.4 2029.31   360.7 2033.52   392.6 2032.99     417 2033.98
   428.8 2032.77   464.4 2034.18   476.7 2032.98   511.8 2035.79   536.9 2042.37
     556  2050.9   587.3 2056.89   620.8 2066.42   650.2 2071.71   668.4 2073.87
#Mann= 4 ,-1,0
       0      .1       0   314.4    .045       0   343.4      .1       0
  621.71     .06       0
Bank Sta=314.4,343.4
XS Rating Curve= 0 ,0
Exp/Cntr=0.3,0.1

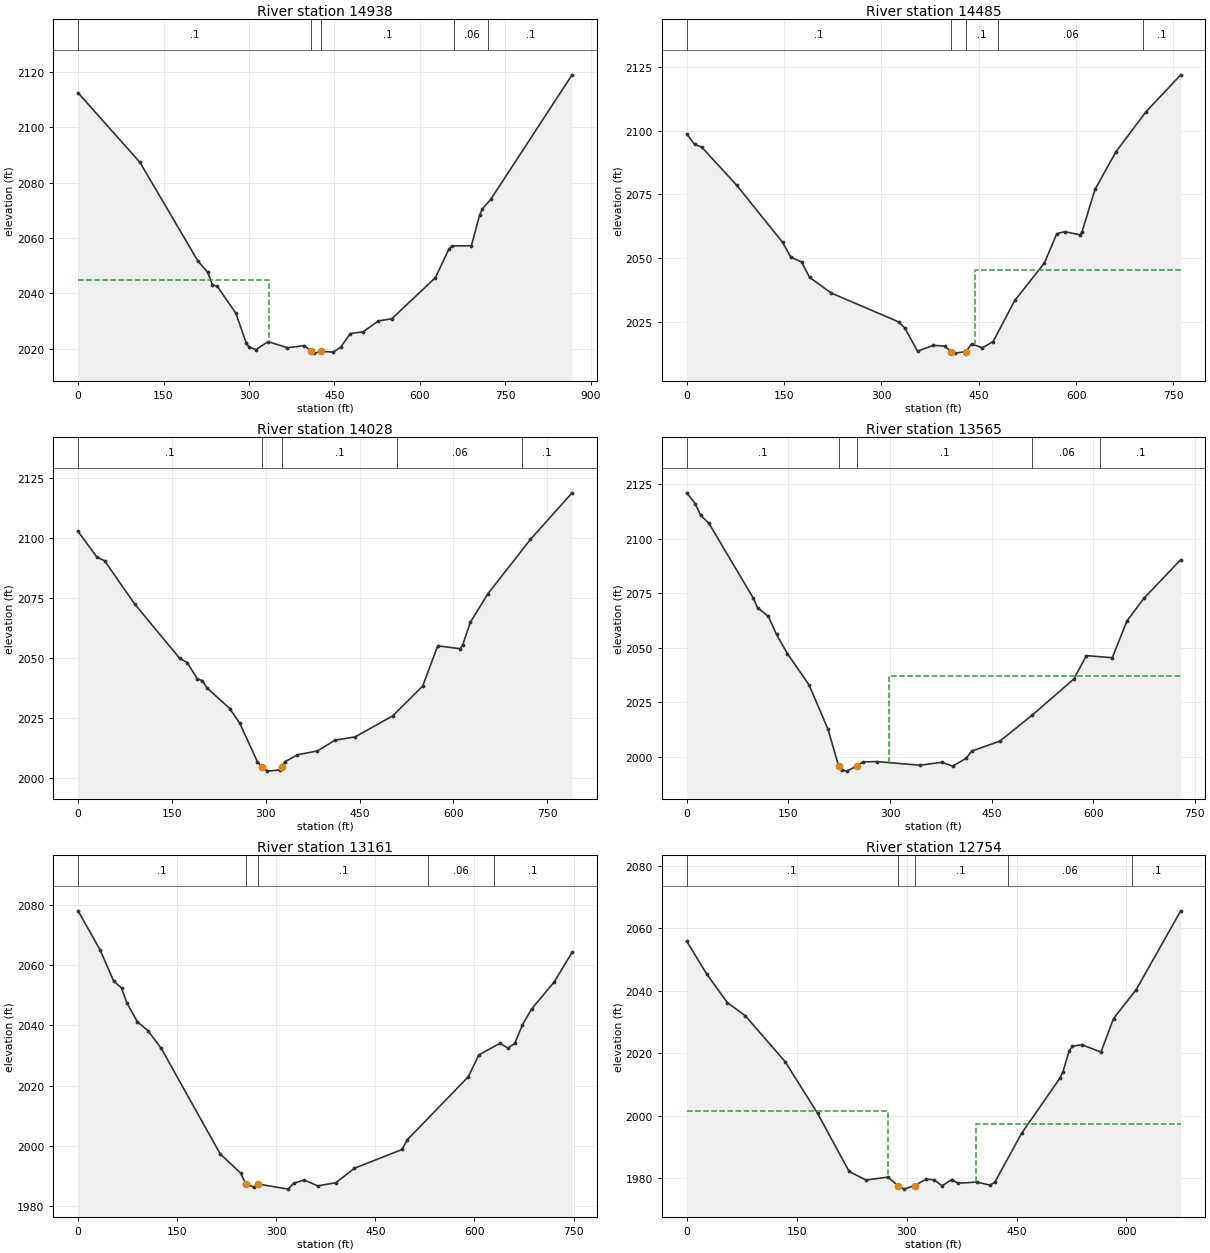
Type RM Length L Ch R = 1 ,14938   ,450.3,453.1,450
XS GIS Cut Line= 3
2236851.64169359694882.9738040582236677.46148574695373.258833576
2236480.70236205695658.720840894
#Sta/Elev= 30
       0 2112.42   108.5 2087.33   210.3  2051.7   227.3 2047.67   235.8 2043.17
   244.3 2042.55   276.9 2032.85   295.2 2022.06   299.5 2020.79   312.2 2019.73
   333.4 2022.63   367.4 2020.39   397.1 2021.19   408.5 2019.12   414.1 2018.46
   426.8 2019.09   448.1 2018.83   460.8 2020.61   477.8 2025.52   500.3 2026.17
   526.9 2030.07   550.8 2030.89   627.1 2045.72   650.6  2055.9   656.2 2057.18
   690.2 2057.21   704.8 2068.33   709.7 2070.57   724.3 2073.98     867 2118.92
#Mann= 5 ,-1,0
       0      .1       0   408.5    .045       0   426.8      .1       0
  660.31     .06       0  720.31      .1       0
#XS Ineff= 2 , 0
          335.02  2044.9
Permanent Ineff=
       F       F
Bank Sta=408.5,426.8
XS Rating Curve= 0 ,0
Exp/Cntr(USF)=0,0
Exp/Cntr=0.3,0.1

Type RM Length L Ch R = 1 ,14485   ,459.4,457.3,448.4
XS GIS Cut Line= 3
2236580.94411378 694827.093426882236426.63555283695368.079225449
2236323.92377346695538.233889818
#Sta/Elev= 30
       0 2098.82      12 2094.75      23 2093.65      77 2078.63   147.8 2056.13
   160.2  2050.4   176.9 2048.44   189.3 2042.41   222.6 2036.24   326.6 2024.89
   335.7 2022.58   355.7 2013.37   380.2 2015.67   397.3 2015.34407.76562013.215
     414 2012.59   430.6 2013.22   438.9 2016.25   455.6 2014.66   472.2 2017.14
   505.5 2033.31   551.2 2048.02   570.3 2059.59   582.8 2060.37   605.9 2059.13
   608.9  2060.1   629.2 2076.99   661.3 2091.73   707.9 2107.56   761.3 2122.07
#Mann= 5 ,-1,0
       0      .1       0407.7656    .045       0   430.6      .1       0
     480     .06       0  702.56      .1       0
#XS Ineff= 2 , 0
                          444.19         2045.14
Permanent Ineff=
       F       F
Bank Sta=407.7656,430.6
XS Rating Curve= 0 ,0
Exp/Cntr(USF)=0,0
Exp/Cntr=0.3,0.1

Type RM Length L Ch R = 1 ,14028   ,463.5,463.2,462.7
XS GIS Cut Line= 2
2236150.08252306694682.9891209652236109.76303051 695471.63839542
#Sta/Elev= 30
       0 2102.55    30.2 2091.81    42.2  2090.4    90.3 2072.38   162.4 2049.68
   174.4 2047.96   190.4 2041.23   198.4 2040.42   206.5 2037.27   242.5 2028.75
   258.5 2022.63   286.6 2006.65  293.612004.518   302.6  2002.7   322.6 2003.19
   325.3 2004.47   330.6 2006.62   350.6  2009.5   382.7 2011.12   410.7  2015.6
   442.8 2016.95   503.1 2025.75   550.9 2038.15   574.9 2054.91     611 2053.69
     615 2055.39     627 2064.71     655 2076.56   723.1 2099.24   789.7 2118.66
#Mann= 5 ,-1,0
       0      .1       0  293.61    .045       0   325.3      .1       0
     510     .06       0     710      .1       0
Bank Sta=293.61,325.3
XS Rating Curve= 0 ,0
Exp/Cntr(USF)=0,0
Exp/Cntr=0.3,0.1

Type RM Length L Ch R = 1 ,13565   ,404.9,403.2,401
XS GIS Cut Line= 3
2235679.15084997 694692.665799182235675.92529057695132.954657924
2235775.91763212695403.901647921
#Sta/Elev= 30
       0 2120.98    12.5    2116    20.5 2110.61    32.5 2107.12    98.3 2072.61
   104.5 2068.26   120.5 2064.26   132.5    2056   148.5 2047.23   180.5 2032.84
   208.5 2012.52  223.991995.846   228.5 1993.83   236.5 1993.29   251.4 1995.77
   260.5 1997.53   280.5 1997.67   344.1    1996   376.5 1997.35   392.4 1995.59
   412.6  1999.2   420.5 2002.51   461.9 2007.01   510.3 2019.08   571.5 2035.62
   589.8 2046.28   628.1 2045.33   649.7 2062.16     675 2072.67   729.1 2090.29
#Mann= 5 ,-1,0
       0      .1       0  223.99    .045       0   251.4      .1       0
   510.3     .06       0   610.3      .1       0
#XS Ineff= 2 , 0
                          299.21         2036.83
Permanent Ineff=
       F       F
Bank Sta=223.99,251.4
XS Rating Curve= 0 ,0
Exp/Cntr(USF)=0,0
Exp/Cntr=0.3,0.1

Type RM Length L Ch R = 1 ,13161   ,401.3,407.7,410.8
XS GIS Cut Line= 3
2235274.34314468694763.6281060842235313.04985754695421.642224647
2235361.43324861695495.830090956
#Sta/Elev= 30
       0 2078.13    33.6 2064.98    53.6 2054.86    65.7 2052.47    73.7 2047.52
    89.7 2041.24   105.7 2038.26   125.8 2032.38   215.1 1997.26     246 1990.89
     254 1987.22     266 1986.27   272.71987.236   318.1 1985.55   326.1 1987.48
   342.1 1988.59   362.7 1986.64   390.2 1987.69   418.3  1992.5   490.4 1998.74
   498.4    2002   590.6 2022.92   606.6 2030.19   638.7 2034.08   650.7 2032.43
   661.1 2034.11   672.6 2040.24   686.8 2045.58   720.7 2054.48   747.7  2064.3
#Mann= 5 ,-1,0
       0      .1       0     254    .045       0   272.7      .1       0
     530     .06       0     630      .1       0
Bank Sta=254,272.7
XS Rating Curve= 0 ,0
Exp/Cntr(USF)=0,0
Exp/Cntr=0.3,0.1

Type RM Length L Ch R = 1 ,12754   ,261.8,263.5,265.7
BEGIN DESCRIPTION:
Structure XS 4
END DESCRIPTION:
XS GIS Cut Line= 3
2235093.71181802694737.8236308462234940.49774629694892.650482273
2234764.70475874695313.585984589
#Sta/Elev= 30
       0 2055.87    27.2 2045.37    55.4 2036.23    79.8 2032.02   134.2 2017.32
   178.5 2000.76   221.5 1982.15   244.4 1979.38   274.7 1980.32   287.8 1977.62
   296.4 1976.47  310.951977.624   326.8 1979.68   337.7 1979.42   348.4 1977.52
   361.4 1979.52   370.1 1978.35   395.8 1978.75   413.5 1977.76   420.3 1978.66
   456.8 1994.32     509 2011.97   513.2 2013.98   521.8 2020.76   526.2 2022.26
   539.2 2022.73   565.2 2020.38   582.3 2031.12   613.1 2040.33     674 2065.63
#Mann= 5 ,-1,0
       0      .1       0   287.8    .045       0  310.95      .1       0
  437.82     .06       0  607.82      .1       0
#XS Ineff= 2 , 0
          274.95 2001.59  395.01         1997.47
Permanent Ineff=
       F       F
Bank Sta=287.8,310.95
XS Rating Curve= 0 ,0
Exp/Cntr(USF)=0,0
Exp/Cntr=0.3,0.1

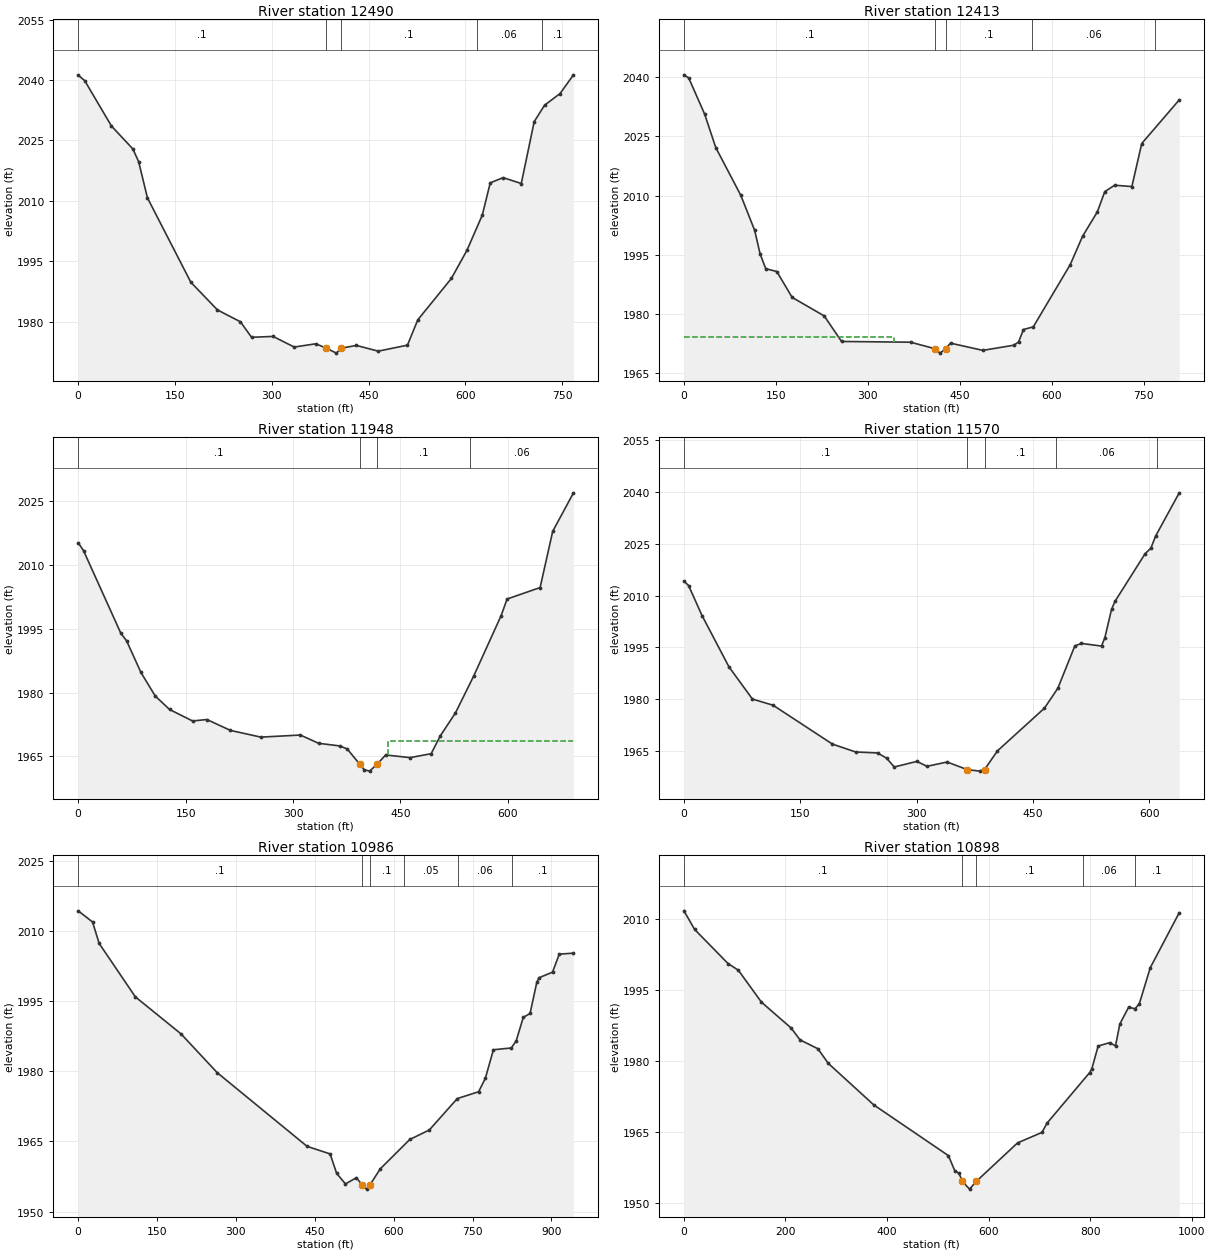
Type RM Length L Ch R = 1 ,12490   ,78.7,77.6,77
BEGIN DESCRIPTION:
Structure XS 3
END DESCRIPTION:
XS GIS Cut Line= 6
2234899.00176101694638.1995444692234744.72892948694719.925600669
 2234755.3103771694811.9841950262234669.80191046694869.255444374
2234603.41069077694973.0674451892234621.30464285695241.941529434
#Sta/Elev= 30
       0 2041.22    10.2 2039.82    51.6 2028.57    84.7 2022.89    93.7 2019.73
   107.3 2010.75   174.6 1989.78   215.9  1982.9   251.5 1979.96   268.7 1976.11
     302 1976.33   334.8 1973.69   368.3  1974.5   384.3 1973.42   400.2 1972.18
   407.6  1973.4   431.1 1974.09     465 1972.67   510.3 1974.16   526.3 1980.44
   578.4 1990.73   602.5 1997.71   626.3 2006.47   638.6 2014.47   658.6 2015.76
   686.7  2014.3   706.7 2029.66   722.8 2033.74   746.8 2036.64   767.6 2041.29
#Mann= 5 ,-1,0
       0      .1       0   384.3    .045       0   407.6      .1       0
  618.15     .06       0  718.15      .1       0
Bank Sta=384.3,407.6
XS Rating Curve= 0 ,0
Exp/Cntr(USF)=0,0
Exp/Cntr=0.3,0.1

Type RM Length L Ch R = 1 ,12413   ,463.9,464.5,461.9
BEGIN DESCRIPTION:
Structure XS 2
END DESCRIPTION:
XS GIS Cut Line= 6
2234834.05428594 694597.51179674 2234679.7814544 694679.23785294
2234690.36290203694771.296447297 2234617.3509134694810.447803518
2234526.82362331 694955.658882242234554.24087825 695234.05626935
#Sta/Elev= 30
       0 2040.62     7.8 2039.82    33.8 2030.64    51.9 2022.17    92.7 2010.07
   115.3 2001.19   124.3 1995.16   133.4 1991.45   151.5 1990.72   176.5 1984.16
   228.8 1979.46   257.1 1972.98   369.7 1972.79   409.3 1971.15     418 1970.02
   426.7 1971.15   434.9 1972.55   487.6 1970.72   538.2 1972.03   545.8 1972.84
   553.9 1976.01   569.9 1976.69   630.2 1992.48   650.3 1999.67   674.4 2005.85
   686.5 2010.99   702.6 2012.61   730.7 2012.28   746.8 2023.19     808 2034.27
#Mann= 5 ,-1,0
       0      .1       0   409.3    .045       0   426.7      .1       0
  568.21     .06       0  768.21      .1       0
#XS Ineff= 2 , 0
          341.93 1974.07
Permanent Ineff=
       F       F
Bank Sta=409.3,426.7
XS Rating Curve= 0 ,0
Exp/Cntr(USF)=0,0
Exp/Cntr=0.3,0.1

Type RM Length L Ch R = 1 ,11948   ,377.3,378.3,378.1
BEGIN DESCRIPTION:
Structure XS 1
END DESCRIPTION:
XS GIS Cut Line= 3
2234226.03633815694413.6549106712234217.97243964694610.414034359
2234051.85613029695076.507368342
#Sta/Elev= 30
       0 2015.15     7.5 2013.28    59.6 1993.89    67.6 1992.14    87.6 1984.72
   107.6 1979.18   127.6 1976.02   159.7 1973.32   179.7 1973.66   212.6 1971.11
   255.1 1969.53   310.3 1970.02   335.7 1968.08   365.5 1967.46   375.8 1966.74
   392.9 1963.24   399.4 1961.88   407.1 1961.55  417.96 1963.27   429.4 1965.34
   463.5 1964.72   492.9 1965.64   505.6  1969.8   526.8 1975.19   552.3 1983.85
   590.5 1997.98     599 2001.94   645.1 2004.63   662.7 2017.83   691.7 2026.86
#Mann= 4 ,-1,0
       0      .1       0   392.9    .045       0  417.96      .1       0
  546.92     .06       0
#XS Ineff= 2 , 0
                          433.16         1968.57
Permanent Ineff=
       F       F
Bank Sta=392.9,417.96
XS Rating Curve= 0 ,0
Exp/Cntr(USF)=0,0
Exp/Cntr=0.3,0.1

Type RM Length L Ch R = 1 ,11570   ,584.2,584.2,583.1
BEGIN DESCRIPTION:
Structure XS 4
END DESCRIPTION:
XS GIS Cut Line= 2
2233940.57433083694355.5948413862233697.04459577 694945.87221245
#Sta/Elev= 30
       0  2014.2       6 2012.91    23.3 2004.23      58 1989.38    88.3 1980.04
   114.9 1978.26   191.4 1967.01   221.3 1964.73   249.6 1964.44   261.3 1962.92
   271.1 1960.38   300.3    1962   313.3 1960.57   339.2 1961.82   365.2 1959.62
   381.4 1959.18   387.5 1959.63   404.1 1965.04   464.7  1977.4     482 1983.18
   503.9 1995.43   512.3 1996.16   538.3 1995.39   542.6 1997.81   551.2    2006
   555.6 2008.31   594.5 2022.14   601.9 2023.72     608 2027.23   638.5 2039.76
#Mann= 5 ,-1,0
       0      .1       0   365.2    .045       0   387.5      .1       0
     480     .06       0     610      .1       0
Bank Sta=365.2,387.5
XS Rating Curve= 0 ,0
Exp/Cntr(USF)=0,0
Exp/Cntr=0.3,0.1

Type RM Length L Ch R = 1 ,10986   ,88.4,87.9,85.2
BEGIN DESCRIPTION:
Structure XS 3
END DESCRIPTION:
XS GIS Cut Line= 6
2233612.29302241693975.8658604652233491.81837865 694074.56797825
2233351.02271063694366.3198264072233323.44417772694515.824504816
2233352.47421236694653.7171693682233292.96264135694810.479356437
#Sta/Elev= 30
       0  2014.3    27.3 2011.92    39.9 2007.33   108.7 1995.91   195.6 1987.99
   264.4  1979.7   435.4 1963.94   479.1 1962.33   491.6 1958.17   508.3 1955.91
   529.1 1957.24   539.9 1955.74   548.4  1954.8   555.21955.764   574.7 1959.16
   630.7 1965.42   667.8 1967.44     721 1974.16   761.6 1975.62   774.4  1978.5
   789.7  1984.6   823.8 1984.98   833.1 1986.52   846.5 1991.52   859.4 1992.35
   872.2    1999   876.5    2000   902.1 2001.18     915 2005.04     942 2005.25
#Mann= 6 ,-1,0
       0      .1       0   539.9    .045       0   555.2      .1       0
  619.43     .05       0   721.8     .06       0  824.37      .1       0
Bank Sta=539.9,555.2
XS Rating Curve= 0 ,0
Exp/Cntr(USF)=0,0
Exp/Cntr=0.3,0.1

Type RM Length L Ch R = 1 ,10898   ,804.2,799.9,787.4
BEGIN DESCRIPTION:
Structure XS 2
END DESCRIPTION:
XS GIS Cut Line= 6
2233560.76471092  693934.49806112233411.26003251 694050.61819967
 2233270.4643645694342.3700478272233242.88583159694491.874726236
2233271.91586623694629.7673907882233212.40429521694786.529577857
#Sta/Elev= 30
       0 2011.77      21 2007.84    86.8 2000.62   107.1 1999.21   152.7 1992.44
   211.1 1986.98   228.7 1984.46   263.9 1982.59   284.1 1979.52   373.8 1970.72
   520.9 1959.98   533.4  1956.8   541.8 1956.24  548.281954.535   562.6 1952.89
   576.1 1954.56   657.1 1962.67   705.2 1964.89   715.1 1966.84   799.2 1977.55
   803.3 1978.31   815.9 1983.17   838.3 1983.86   850.1 1983.21   858.6 1987.83
   875.8 1991.36   888.6 1991.06     897 1992.12   918.5 1999.73   975.6 2011.38
#Mann= 5 ,-1,0
       0      .1       0  548.28    .045       0   576.1      .1       0
  785.36     .06       0  887.93      .1       0
Bank Sta=548.28,576.1
XS Rating Curve= 0 ,0
Exp/Cntr(USF)=0,0
Exp/Cntr=0.3,0.1

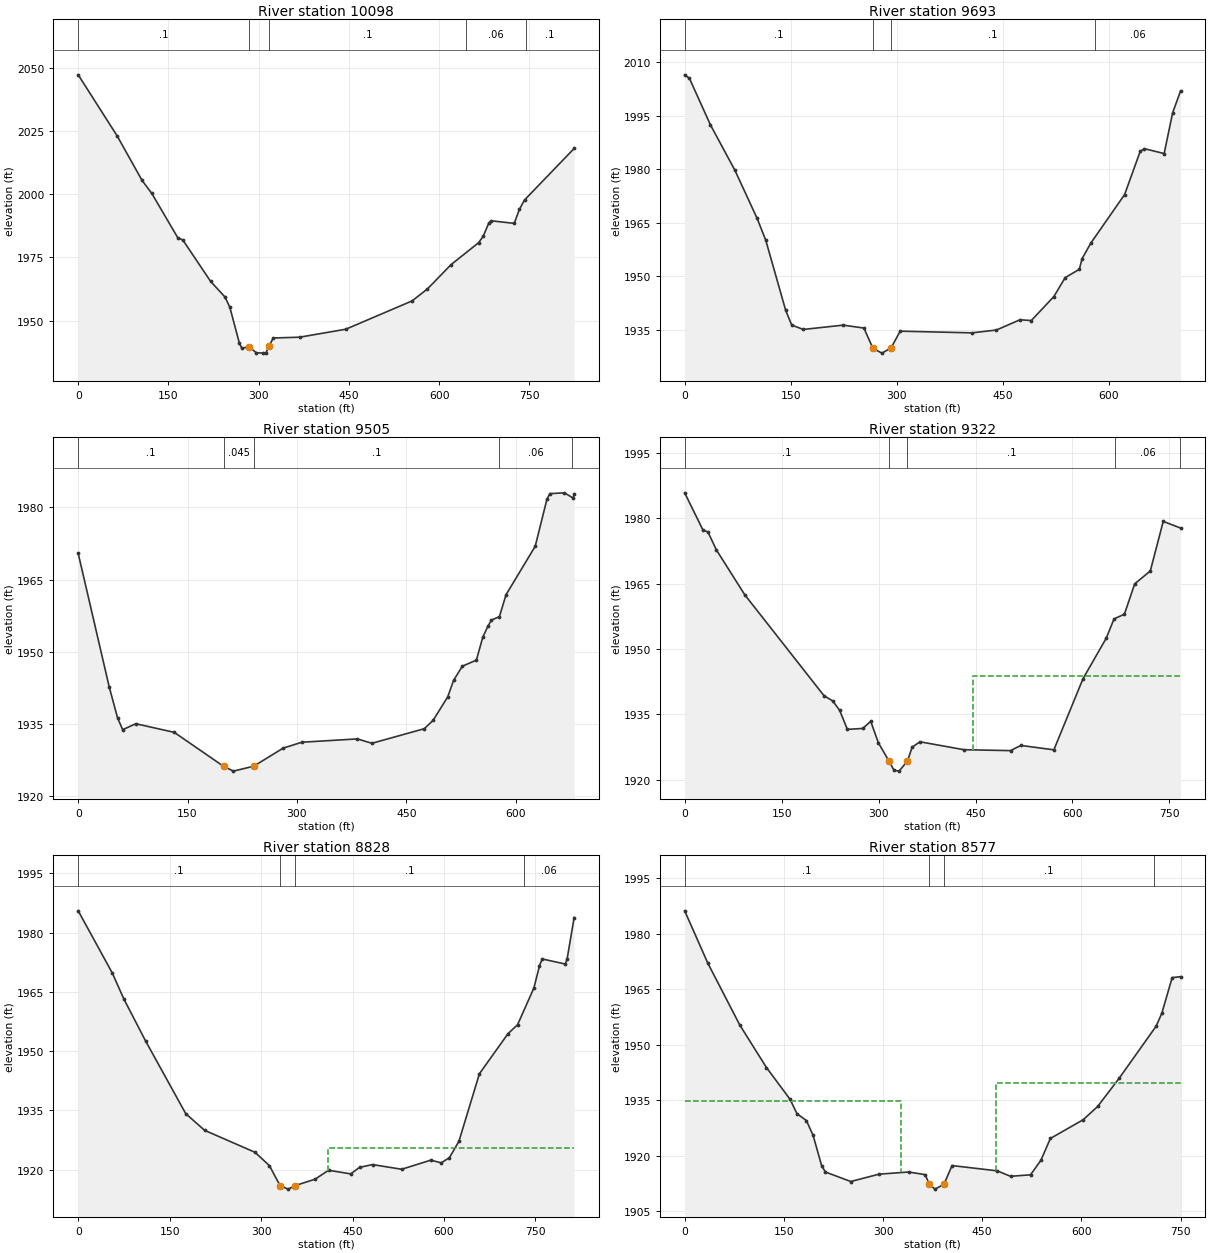
Type RM Length L Ch R = 1 ,10098   ,398.1,405.1,408.4
BEGIN DESCRIPTION:
Structure XS 1
END DESCRIPTION:
XS GIS Cut Line= 4
2232911.94343666693783.5418809592232845.17435698693992.558130385
2232848.07736045694277.0524698812232740.66623227694578.964830163
#Sta/Elev= 30
       0 2047.33      65 2023.03   106.1 2005.52   122.1 2000.45   165.5 1982.82
   173.9 1981.93     220 1965.56     244 1959.33     252 1955.31     268 1940.98
     272 1939.04     284 1939.67     296 1937.26     308 1937.11     312 1937.28
  317.591939.915     324  1943.1   368.1 1943.42   444.8 1946.58     555 1957.79
   580.5 1962.53   619.8 1972.17   665.4 1980.81   673.1 1983.33   682.4 1988.54
   686.6 1989.52   724.8  1988.5   733.3 1994.01   741.9 1997.76   824.4 2018.17
#Mann= 5 ,-1,0
       0      .1       0     284    .045       0  317.59      .1       0
  643.93     .06       0  743.93      .1       0
Bank Sta=284,317.59
XS Rating Curve= 0 ,0
Exp/Cntr(USF)=0,0
Exp/Cntr=0.3,0.1

Type RM Length L Ch R = 1 ,9693    ,198.6,187.5,175.6
XS GIS Cut Line= 3
2232549.08742058693750.8530330242232411.70293501694127.339363665
2232405.09791167694428.528428177
#Sta/Elev= 30
       0 2006.42     6.7 2005.44    36.5 1992.39    71.2 1979.65   102.4 1966.28
   114.8 1960.08     143 1940.44   151.5 1936.34   167.9 1935.11   224.4 1936.32
   253.7  1935.5   266.5  1929.8   279.2 1928.48     292 1929.91   305.1 1934.63
   406.6 1934.16   441.3 1934.95   474.6 1937.82   490.6  1937.6   522.6 1944.33
   538.6 1949.63   558.6 1951.95   562.6 1954.97   574.9 1959.29   622.7 1972.89
   644.8 1984.98   650.7 1985.74   678.7 1984.37   690.7 1995.78     702 2001.95
#Mann= 4 ,-1,0
       0      .1       0   266.5    .045       0     292      .1       0
  580.77     .06       0
Bank Sta=266.5,292
XS Rating Curve= 0 ,0
Exp/Cntr(USF)=0,0
Exp/Cntr=0.3,0.1

Type RM Length L Ch R = 1 ,9505    ,178.6,183.3,187.4
XS GIS Cut Line= 6
2232292.05803648693739.1796905742232266.94279441693895.996811744
2232268.78049505 693930.913123882232280.41926576693976.243072968
2232306.14707471694038.1123278052232310.43504286694410.552990584
#Sta/Elev= 30
       0 1970.43    42.5 1942.75      54 1936.29      61 1933.85      79 1935.09
   131.7  1933.3   199.31926.258   212.9 1925.25  240.71 1926.27   281.1 1930.02
   306.8 1931.25   382.9 1931.94   402.9 1931.03   474.8 1934.06   486.9 1935.81
   506.9 1940.67   514.9 1944.08   526.9 1947.03   546.2 1948.29   554.9 1953.02
     562 1955.34   566.9  1956.6   577.8 1957.33   586.9 1961.88   626.9 1971.93
   642.9 1981.65   646.9 1982.85   666.9 1983.02   678.9 1981.94   680.3 1982.68
#Mann= 5 ,-1,0
       0      .1       0   199.3    .045       0  240.71      .1       0
   577.8     .06       0   677.8      .1       0
Bank Sta=199.3,240.71
XS Rating Curve= 0 ,0
Exp/Cntr(USF)=0,0
Exp/Cntr=0.3,0.1

Type RM Length L Ch R = 1 ,9322    ,500.8,494.1,487.5
XS GIS Cut Line= 3
2232134.23601998 693645.729386592232090.69096802693867.809151606
2232119.55843752694407.982912741
#Sta/Elev= 30
       0  1985.8      28 1977.35    36.1  1976.8      49 1972.73      93 1962.42
   215.5  1939.3     229 1938.09   239.7 1935.96   251.7 1931.57   275.7 1931.79
   287.8 1933.43   299.8 1928.46   316.5 1924.21   323.8  1922.2   331.7    1922
   344.7 1924.31   351.9 1927.47   363.9 1928.73     432 1926.91   504.1  1926.7
   520.1 1927.89   571.2 1926.88   616.2 1943.16   652.3  1952.5   664.3  1956.9
   680.3 1957.97   696.3 1964.94   720.4 1967.89   740.4 1979.25   767.3 1977.72
#Mann= 5 ,-1,0
       0      .1       0   316.5    .045       0   344.7      .1       0
  666.31     .06       0  766.31      .1       0
#XS Ineff= 2 , 0
                          445.92         1943.78
Permanent Ineff=
       F       F
Bank Sta=316.5,344.7
XS Rating Curve= 0 ,0
Exp/Cntr(USF)=0,0
Exp/Cntr=0.3,0.1

Type RM Length L Ch R = 1 ,8828    ,250.2,250.4,248.4
XS GIS Cut Line= 6
2231473.01124755693767.8139420652231585.20340152693977.639035199
2231604.91376191694032.620566838  2231642.887423694091.841106022
2231677.16711722694120.8470011372231856.60763726694480.181630672
#Sta/Elev= 30
       0 1985.49      56 1969.72    74.6 1963.26   110.4 1952.58   176.4 1934.14
   207.3 1929.93   289.9 1924.37   313.6    1921  331.17 1915.91   344.5 1915.04
   356.21915.952   388.3 1917.54   410.7 1919.81   447.1  1918.9   461.4 1920.55
   482.9 1921.25   530.6 1920.07   578.3 1922.37   595.5  1921.7   608.9 1923.01
   624.5 1927.15   658.1 1944.25   705.1 1954.41   720.7 1956.66   747.5 1965.97
   756.5 1971.49     761 1973.31     799 1972.02     802 1973.33   813.5 1983.79
#Mann= 4 ,-1,0
       0      .1       0  331.17    .045       0   356.2      .1       0
  731.85     .06       0
#XS Ineff= 2 , 0
                          408.92         1925.55
Permanent Ineff=
       F       F
Bank Sta=331.17,356.2
XS Rating Curve= 0 ,0
Exp/Cntr(USF)=0,0
Exp/Cntr=0.3,0.1

Type RM Length L Ch R = 1 ,8577    ,653.3,650.6,643.5
XS GIS Cut Line= 2
2231226.47485508693933.1470326722231673.53738858694535.520251504
#Sta/Elev= 30
       0 1986.26    34.9 1972.15    83.4 1955.37   123.7  1943.9   159.4 1935.31
   169.9  1931.4   184.1 1929.57   194.3 1925.54   207.1  1917.4   212.8 1915.66
   251.2 1913.09   293.9 1915.07   338.6 1915.66   363.7 1914.95   370.1 1912.34
   378.6 1911.03   392.1 1912.32   404.4  1917.4   472.7 1915.97   492.8  1914.5
   523.1  1914.9   538.8 1918.83   553.1 1924.72   602.8  1929.8   624.6 1933.37
   657.6 1941.11   713.2 1955.11   721.8 1958.64   737.3  1968.2   750.1 1968.46
#Mann= 4 ,-1,0
       0      .1       0   370.1    .045       0   392.1      .1       0
     710     .06       0
#XS Ineff= 2 , 0
          326.93 1934.83  470.18         1939.66
Permanent Ineff=
       F       F
Bank Sta=370.1,392.1
XS Rating Curve= 0 ,0
Exp/Cntr(USF)=0,0
Exp/Cntr=0.3,0.1