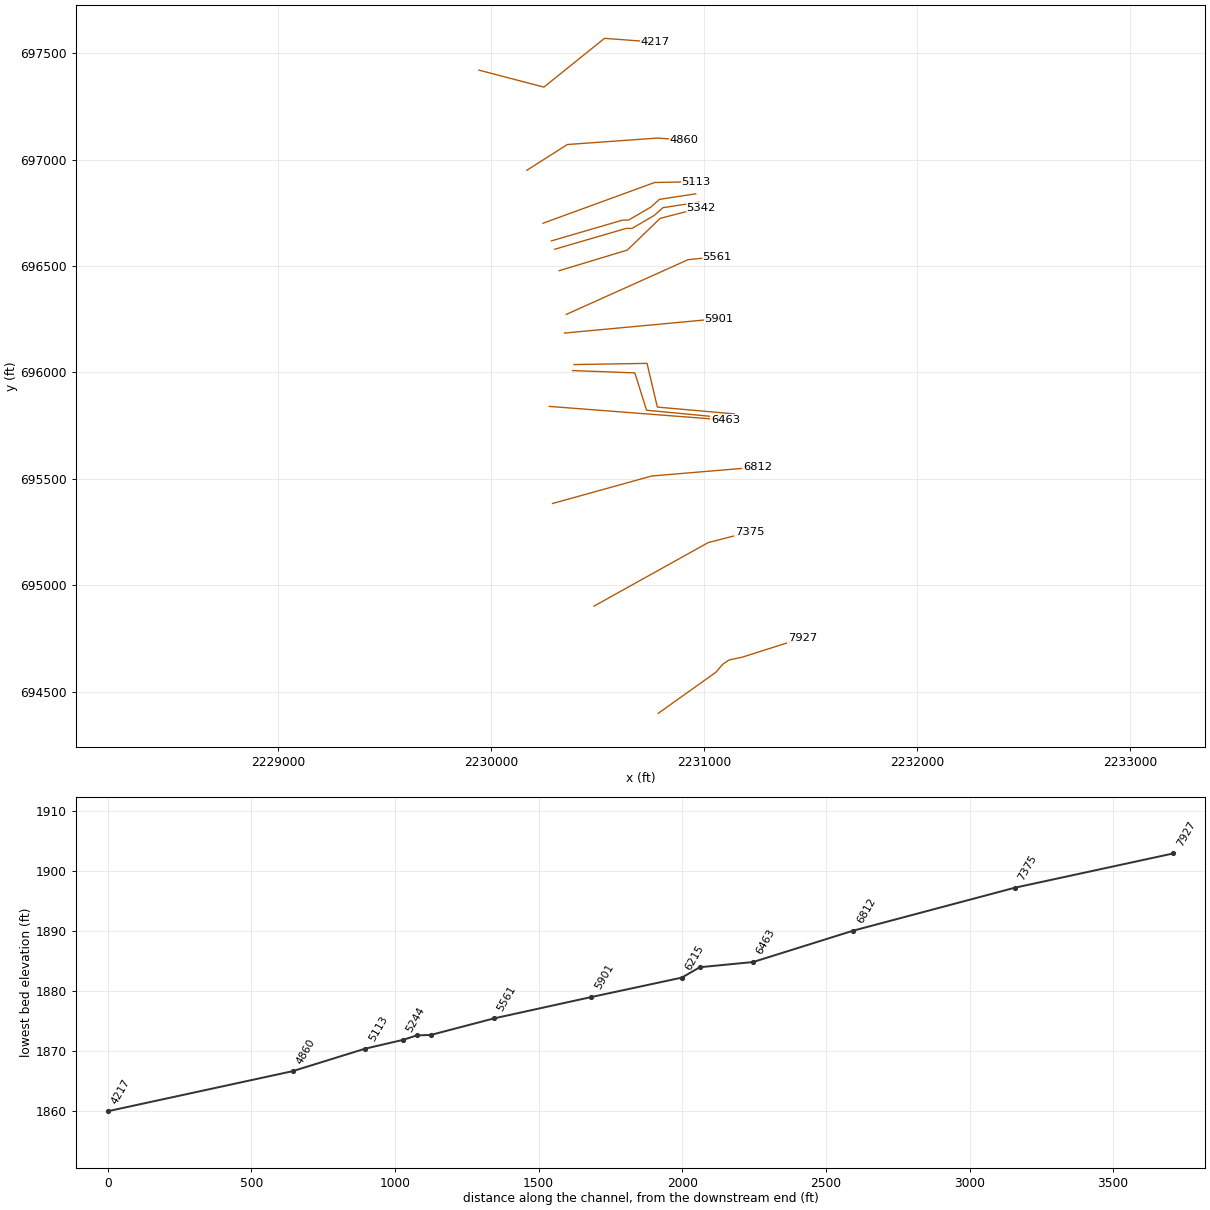
HEC-RAS study LAURELCK.prj: LAURELCK

--- LAURELCK.g01 (geometry) --- (continued)

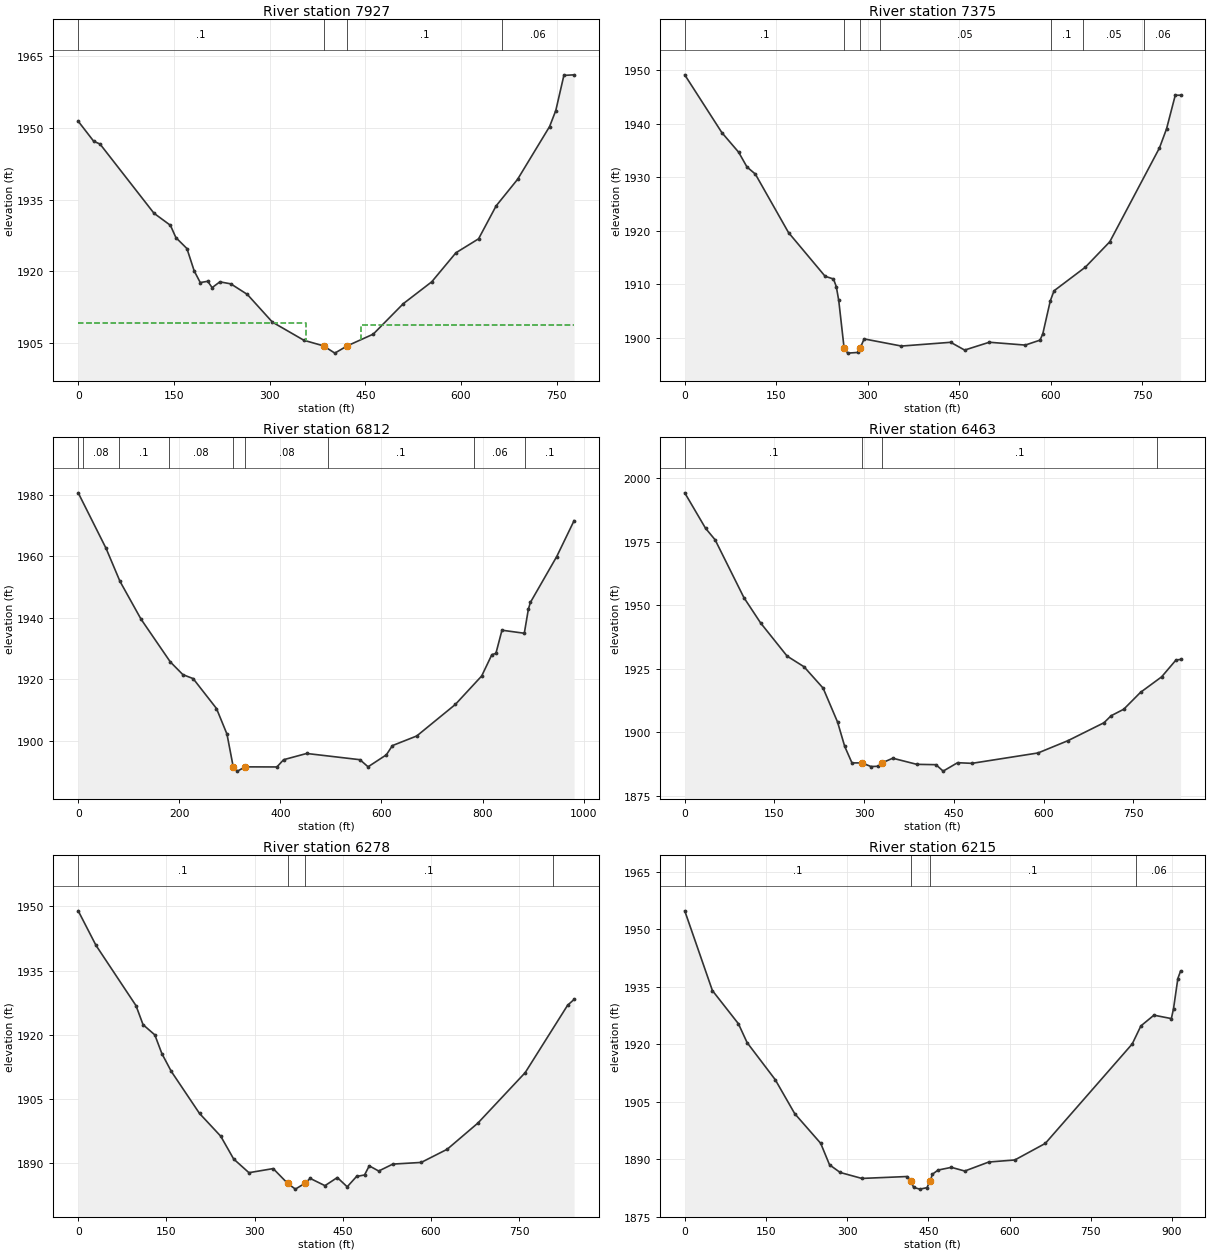
Type RM Length L Ch R = 1 ,7927    ,552.5,551.9,553
XS GIS Cut Line= 6
 2230784.3626403694399.3914532332231056.20267957694593.117223282
2231086.96578826694629.3383028712231116.24035943694649.681648941
 2231181.7360102694664.0708449422231460.66642205 694752.84044284
#Sta/Elev= 30
       0 1951.39    24.3  1947.2    34.2 1946.62   118.7 1932.16   144.5 1929.63
   153.1 1927.06   170.4 1924.77   181.8 1920.09   191.3 1917.66     203 1917.93
   209.9  1916.6     222 1917.81   239.2 1917.39   265.1 1915.18   304.3  1909.4
   353.7  1905.6   384.51904.423   402.2 1902.91  421.53 1904.42   462.4 1906.88
   509.6 1913.26   554.1 1917.82     592 1923.89   627.5 1926.81     655 1933.69
   688.6 1939.24   738.8 1950.28   748.5 1953.62   761.2 1960.97   777.2 1961.09
#Mann= 4 ,-1,0
       0      .1       0   384.5    .045       0  421.53      .1       0
  664.52     .06       0
#XS Ineff= 2 , 0
          357.55 1909.16  442.87         1908.78
Permanent Ineff=
       F       F
Bank Sta=384.5,421.53
XS Rating Curve= 0 ,0
Exp/Cntr=0.3,0.1

Type RM Length L Ch R = 1 ,7375    ,555.6,562.6,553.7
XS GIS Cut Line= 3
2230482.92868842694902.9431007472231019.45949838695201.305896014
2231212.71386052695250.926290785
#Sta/Elev= 30
       0  1949.1    60.9 1938.32    88.4 1934.67   102.1 1931.91   115.8 1930.59
   170.2 1919.68   230.3 1911.52     244 1911.02   248.6 1909.59   252.6 1907.03
   261.4 1898.14   267.3 1897.19   284.4 1897.32   287.9 1898.18   294.3 1899.84
   355.5 1898.51   436.2 1899.21   459.1 1897.76   499.6 1899.22   558.5 1898.69
   582.7 1899.61   587.3 1900.78   599.6 1906.93   605.8 1908.82   657.1 1913.22
   697.2 1917.96   778.7 1935.47   790.3 1939.02   804.6 1945.29   813.4  1945.3
#Mann= 7 ,-1,0
       0      .1       0   261.4    .045       0   287.9      .1       0
     320     .05       0     600      .1       0  653.91     .05       0
  753.91     .06       0
Bank Sta=261.4,287.9
XS Rating Curve= 0 ,0
Exp/Cntr=0.3,0.1

Type RM Length L Ch R = 1 ,6812    ,354.9,349.3,345.9
XS GIS Cut Line= 3
2230288.57259952 695384.888547142230754.24958477695514.040630976
2231250.38573828695555.703504005
#Sta/Elev= 30
       0 1980.68    55.2 1962.56    82.6 1951.86   124.1 1939.58   182.2 1925.61
   207.1 1921.46   227.4 1920.17   273.6 1910.42   294.3  1902.1  306.74  1891.4
   315.1 1890.03   330.4 1891.42   393.1 1891.39   406.4 1893.75     452 1895.78
   557.4 1893.75   573.5 1891.44   609.6 1895.33   621.7 1898.35   669.8 1901.48
   746.1 1911.74   798.3 1921.03   818.4 1927.97   826.4 1928.37   838.4 1935.93
   882.6 1934.94   890.6 1942.74   894.6 1944.97   946.8 1959.94   981.1 1971.62
#Mann= 9 ,-1,0
       0      .1       0      10     .08       0      80      .1       0
     180     .08       0  306.74    .045       0   330.4     .08       0
  493.25      .1       0  783.25     .06       0  883.25      .1       0
Bank Sta=306.74,330.4
XS Rating Curve= 0 ,0
Exp/Cntr(USF)=0,0
Exp/Cntr=0.3,0.1

Type RM Length L Ch R = 1 ,6463    ,205.3,185,168.4
XS GIS Cut Line= 2
2230273.54704371695840.7129983352231099.84775542695776.998244661
#Sta/Elev= 30
       0 1994.13    34.7 1980.23    50.8 1975.66    98.9 1952.96     127 1942.95
   171.1 1929.98   199.4 1925.79   231.3 1917.39   255.4 1904.08   267.4 1894.49
   279.5 1888.02   296.3 1888.02   311.2  1886.6   323.6 1886.69  329.491888.012
   347.7 1889.86   387.8 1887.46   419.9 1887.32   431.9 1884.79     456  1888.1
     480 1887.85   590.5 1891.93   640.5 1896.76   700.7  1903.8   712.7 1906.56
   733.7  1909.1   761.8 1915.75     797 1921.82   821.1 1928.46   828.8 1928.66
#Mann= 4 ,-1,0
       0      .1       0   296.3    .045       0  329.49      .1       0
     790     .06       0
Bank Sta=296.3,329.49
XS Rating Curve= 0 ,0
Exp/Cntr(USF)=0,0
Exp/Cntr=0.3,0.1

Type RM Length L Ch R = 1 ,6278    ,65.7,63,61.5
XS GIS Cut Line= 4
 2230381.9909248696009.0541251732230674.79789324695998.027921341
 2230729.9289124695822.8337937842231095.01877262695787.917481648
#Sta/Elev= 30
       0 1948.97    30.2 1940.91    98.3 1926.81   110.3 1922.36   130.3 1919.98
   142.3  1915.6   158.3 1911.45   206.3 1901.62   242.4  1896.3   264.4 1890.97
   290.4 1887.77   331.6 1888.73  356.33 1885.26   369.4 1883.93   385.31885.269
   394.5 1886.44   419.7 1884.74   440.7 1886.64   457.5 1884.47   473.4 1886.89
     487 1887.24     495 1889.37   511.1 1888.16   535.1 1889.78   583.4 1890.17
   627.6 1893.25   679.8 1899.37   760.2 1911.15   832.3 1926.89   843.4 1928.27
#Mann= 4 ,-1,0
       0      .1       0  356.33    .045       0   385.3      .1       0
  806.68     .06       0
Bank Sta=356.33,385.3
XS Rating Curve= 0 ,0
Exp/Cntr(USF)=0,0
Exp/Cntr=0.3,0.1

Type RM Length L Ch R = 1 ,6215    ,282.8,314.3,330.3
XS GIS Cut Line= 4
2230389.03544392696037.2322016332230732.07289648696042.745303549
2230780.46567996695837.5353988932231141.26757203695805.681921156
#Sta/Elev= 30
       0 1954.76    51.1 1933.97    99.2 1925.31   115.2  1920.4   167.2 1910.73
   203.2 1901.87   251.2 1894.13   267.5 1888.53   287.2 1886.53   327.2 1884.98
     411 1885.48   417.6 1884.38   422.8 1882.64   434.3 1882.19   447.4 1882.56
  453.53 1884.38   457.5 1886.07     468 1887.16   492.6 1887.87   517.3 1886.91
   561.7 1889.26   609.8 1889.79   666.1 1894.11   826.7 1920.05   842.7 1924.75
   866.8 1927.55     899 1926.66     903 1929.27     911 1937.11   916.1 1939.09
#Mann= 4 ,-1,0
       0      .1       0   417.6    .045       0  453.53      .1       0
  833.92     .06       0
Bank Sta=417.6,453.53
XS Rating Curve= 0 ,0
Exp/Cntr(USF)=0,0
Exp/Cntr=0.3,0.1

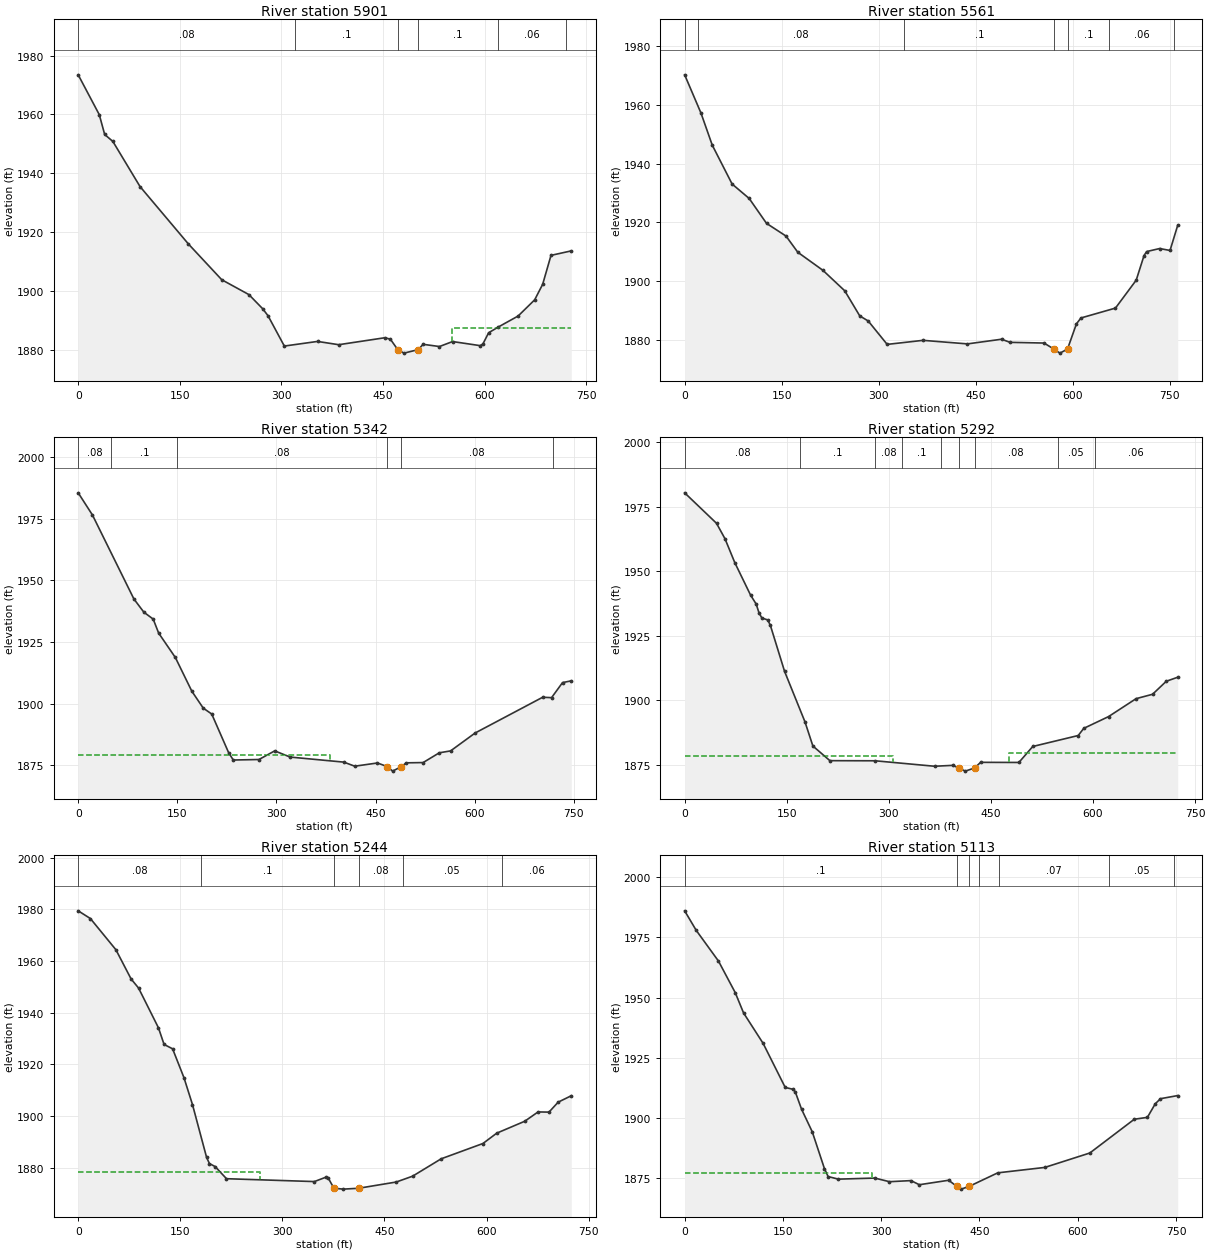
Type RM Length L Ch R = 1 ,5901    ,338.9,339.7,342.8
XS GIS Cut Line= 2
 2230345.2261416696185.1708853832231069.98146463696252.867811161
#Sta/Elev= 30
       0 1973.44    31.1 1959.93    39.1 1953.19    51.2 1950.82    91.3  1935.5
   162.8 1915.99   211.9 1903.88     252 1898.83   272.1 1894.09   280.2 1891.67
   304.3 1881.36   353.3 1882.93   384.6 1881.82   452.9 1884.19   460.9 1883.67
  471.821880.134     481 1878.96  501.94 1880.15   509.2 1881.95   533.3  1881.2
   552.7 1882.89   593.5  1881.5   597.5 1882.08   605.9 1885.87     620  1887.8
   649.4 1891.55   673.9 1897.06   685.7 1902.33     698 1912.15   727.9 1913.67
#Mann= 6 ,-1,0
       0     .08       0     320      .1       0  471.82    .045       0
  501.94      .1       0     620     .06       0     720      .1       0
#XS Ineff= 2 , 0
                          552.42         1887.63
Permanent Ineff=
       F       F
Bank Sta=471.82,501.94
XS Rating Curve= 0 ,0
Exp/Cntr(USF)=0,0
Exp/Cntr=0.3,0.1

Type RM Length L Ch R = 1 ,5561    ,215.9,219,222.9
XS GIS Cut Line= 3
 2230353.1904858696272.7786716842230924.63218281 696529.62877243
2231060.02603437696543.566374796
#Sta/Elev= 30
       0 1970.31    25.2 1957.29    42.7 1946.32    73.4 1933.06    99.8 1928.14
   126.6 1919.65   156.8 1915.31     175 1909.79   213.8 1903.64   247.6 1896.65
   270.8 1888.09   283.9 1886.35   313.2 1878.37   368.7 1879.75   437.4 1878.54
   490.1 1880.13   503.2 1879.07   555.8 1878.83   571.4 1876.73   580.4 1875.39
  592.121876.769   605.9 1885.36   612.9 1887.38   666.3 1890.75   698.4 1900.28
   710.5 1908.67   714.5 1910.03   734.6 1911.06   750.7 1910.41   762.6 1919.01
#Mann= 7 ,-1,0
       0      .1       0      20     .08       0     340      .1       0
   571.4    .045       0  592.12      .1       0  656.51     .06       0
  756.51      .1       0
Bank Sta=571.4,592.12
XS Rating Curve= 0 ,0
Exp/Cntr(USF)=0,0
Exp/Cntr=0.3,0.1

Type RM Length L Ch R = 1 ,5342    ,56,49.8,50.7
XS GIS Cut Line= 4
2230319.49840819696477.9487368052230639.25609724696574.698937166
2230793.62295089696723.5526889012230984.92758738696773.170606146
#Sta/Elev= 30
       0 1985.44    21.6 1976.44    84.3 1942.42    99.4 1937.05   113.5 1934.26
   121.8 1928.57     147 1918.71     172 1905.02   189.2 1898.19   202.1 1895.78
   227.7  1880.1   234.7 1877.14   273.6 1877.35   297.4 1880.85   320.8 1878.34
     402 1876.29   418.5 1874.64   452.9 1875.94  467.56  1874.5   475.9 1872.64
   489.2 1874.51   496.5    1876     522 1876.11   546.5 1880.07   563.6 1880.84
   600.7 1888.09   702.9 1902.58   716.4 1902.42     733 1908.53   746.2 1909.23
#Mann= 6 ,-1,0
       0     .08       0      50      .1       0     150     .08       0
  467.56    .045       0   489.2     .08       0  718.52     .06       0
#XS Ineff= 2 , 0
           381.6    1879
Permanent Ineff=
       F       F
Bank Sta=467.56,489.2
XS Rating Curve= 0 ,0
Exp/Cntr(USF)=0,0
Exp/Cntr=0.3,0.1

Type RM Length L Ch R = 1 ,5292    ,47.3,48.4,43
XS GIS Cut Line= 6
2230299.29396485696578.8155090352230633.33270424696676.329923638
2230661.34216376696676.3299236382230766.11829009696737.535779613
2230806.57639827696773.8443382422230976.70793013696799.779022977
#Sta/Elev= 30
       0 1980.47    46.8 1968.66    59.3 1962.64    73.6 1953.44    96.8 1940.83
   105.1 1937.33   109.3 1933.88   113.4 1931.95     122 1931.18   125.9 1929.11
   146.8 1911.24   176.8 1891.65   188.4 1882.29   213.4 1876.61     280 1876.56
   367.2 1874.44   394.2 1874.79   402.8 1873.75   412.4 1872.55   425.9 1873.76
   434.9 1875.96   491.1 1875.91   511.5 1882.11   578.3 1886.36   586.4 1889.13
   622.8 1893.69   663.3 1900.65   687.5 1902.35   707.7  1907.4   724.5 1908.96
#Mann= 9 ,-1,0
       0     .08       0     170      .1       0     280     .08       0
     320      .1       0  376.68     .08       0   402.8    .045       0
   425.9     .08       0  548.03     .05       0  602.39     .06       0
#XS Ineff= 2 , 0
          305.42  1878.4   477.1         1879.67
Permanent Ineff=
       F       F
Bank Sta=402.8,425.9
XS Rating Curve= 0 ,0
Exp/Cntr(USF)=0,0
Exp/Cntr=0.3,0.1

Type RM Length L Ch R = 1 ,5244    ,134.6,130.5,124
XS GIS Cut Line= 6
2230283.03111873696617.9008777222230617.06985812696715.415292325
2230645.07931764696715.4152923252230749.85544397  696776.6211483
2230790.31355215696812.9297069292230960.44508401696838.864391664
#Sta/Elev= 30
       0 1979.41    17.9 1976.43    55.4 1964.37    77.7 1953.08    88.7 1949.55
   117.9 1934.19   126.2 1927.74   138.7 1926.06   155.4  1914.9   167.9 1904.52
   188.7 1884.03   192.9 1881.67   201.2 1880.53   217.9 1875.83     347 1874.72
   363.4 1876.36   367.5 1876.03  375.78 1872.15   389.5  1871.8   411.9 1872.13
   467.4 1874.55   491.4 1876.81   533.4 1883.53   594.7 1889.44     615 1893.44
   656.1 1898.04   675.7 1901.65   691.8 1901.58   705.2 1905.42   724.5 1907.91
#Mann= 6 ,-1,0
       0     .08       0     180      .1       0  375.78    .045       0
   411.9     .08       0  476.68     .05       0  622.39     .06       0
#XS Ineff= 2 , 0
          266.69 1878.43
Permanent Ineff=
       F       F
Bank Sta=375.78,411.9
XS Rating Curve= 0 ,0
Exp/Cntr(USF)=0,0
Exp/Cntr=0.3,0.1

Type RM Length L Ch R = 1 ,5113    ,258.6,253.1,251.1
XS GIS Cut Line= 3
2230243.68075293696700.8621729282230767.33638468696892.006433949
2230962.46281781696895.988606053
#Sta/Elev= 30
       0 1986.03    17.6 1977.93    51.6 1965.15    77.2 1952.03    89.9 1943.59
   119.8 1930.92   153.5 1912.61     166 1911.81   169.1  1910.6   178.4 1903.59
   194.8 1894.15   213.4 1878.84     219 1875.57   234.6  1874.5   290.1 1874.95
   312.6 1873.44   345.4 1873.89   358.2 1872.18     403 1874.04   415.5 1871.46
   422.1 1870.35   434.2 1871.49   477.9 1877.12   549.7 1879.37   618.4 1885.36
   686.3  1899.4   706.3 1900.18   718.3 1905.82   726.3 1907.94   752.6 1909.24
#Mann= 7 ,-1,0
       0      .1       0   415.5    .045       0   434.2      .1       0
     450     .05       0     480     .07       0  647.45     .05       0
  747.45     .06       0
#XS Ineff= 2 , 0
          285.67 1877.24
Permanent Ineff=
       F       F
Bank Sta=415.5,434.2
XS Rating Curve= 0 ,0
Exp/Cntr(USF)=0,0
Exp/Cntr=0.3,0.1

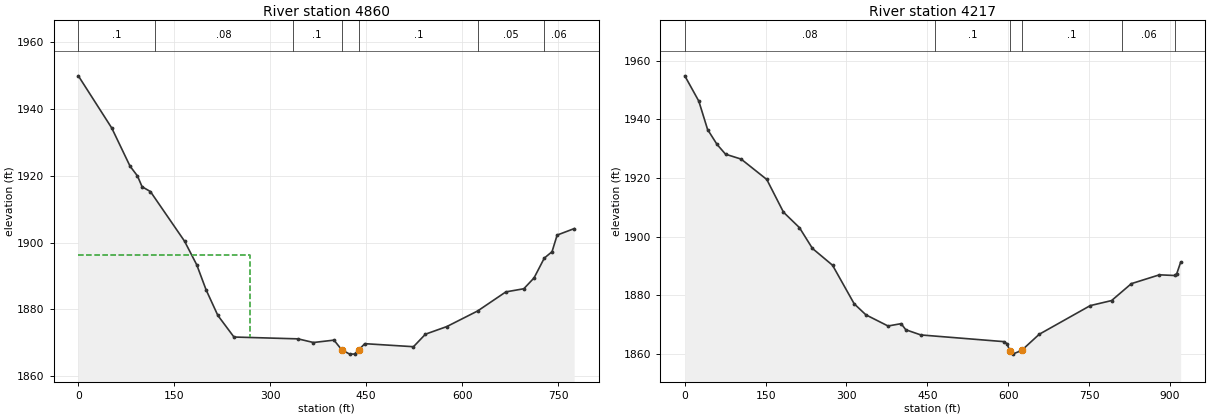
Type RM Length L Ch R = 1 ,4860    ,629.9,643.4,646.8
XS GIS Cut Line= 4
2230168.01948294696949.7479294652230358.14248101697070.438608144
2230780.44430508697100.7640905552230906.71240834 697091.33196338
#Sta/Elev= 30
       0  1949.9    52.3 1934.26    80.8 1922.87    92.4 1919.94    99.7 1916.69
   112.7 1915.26     166 1900.42   185.2  1893.3   199.7 1885.86   218.1 1878.18
   243.3 1871.71   343.5 1871.16   367.6 1870.07   399.7 1870.78   411.7 1867.91
   424.2 1866.59   431.8 1866.62  438.651867.897   447.8 1869.72     524 1868.81
   542.7 1872.56   576.1 1874.84   624.3 1879.51   668.4 1885.22   696.5 1886.16
   712.5 1889.41   728.5 1895.33   740.6 1897.25   748.6 1902.23   775.2 1904.16
#Mann= 7 ,-1,0
       0      .1       0     120     .08       0   335.2      .1       0
   411.7    .045       0  438.65      .1       0   625.2     .05       0
  728.58     .06       0
#XS Ineff= 2 , 0
          268.58 1896.21
Permanent Ineff=
       F       F
Bank Sta=411.7,438.65
XS Rating Curve= 0 ,0
Exp/Cntr(USF)=0,0
Exp/Cntr=0.3,0.1

Type RM Length L Ch R = 1 ,4217    ,331.8,323.9,313.4
XS GIS Cut Line= 4
2229943.02675903697419.6442378082230247.66292503697340.000795716
2230532.38823051 697568.975691732230771.31855679 697551.05591726
#Sta/Elev= 30
       0  1954.8      26 1946.17    42.3 1936.49    59.7 1931.44    75.6 1928.08
   104.5 1926.41   152.1 1919.46   183.1  1908.3   212.7 1903.04   236.8 1895.95
   274.1 1890.22   314.3 1877.06     336 1873.31   377.1  1869.5   401.4  1870.3
     410 1868.22     438 1866.45     592 1864.17   597.6  1863.5     603 1861.13
   608.1 1859.91  624.781861.148   657.5 1866.67   752.2 1876.45   791.8 1878.17
   828.5 1883.94   880.6 1886.95   908.7 1886.72   912.7 1887.33   919.9 1891.21
#Mann= 6 ,-1,0
       0     .08       0  464.88      .1       0     603    .045       0
  624.78      .1       0  810.25     .06       0  910.25      .1       0
Bank Sta=603,624.78
XS Rating Curve= 0 ,0
Exp/Cntr(USF)=0,0
Exp/Cntr=0.3,0.1