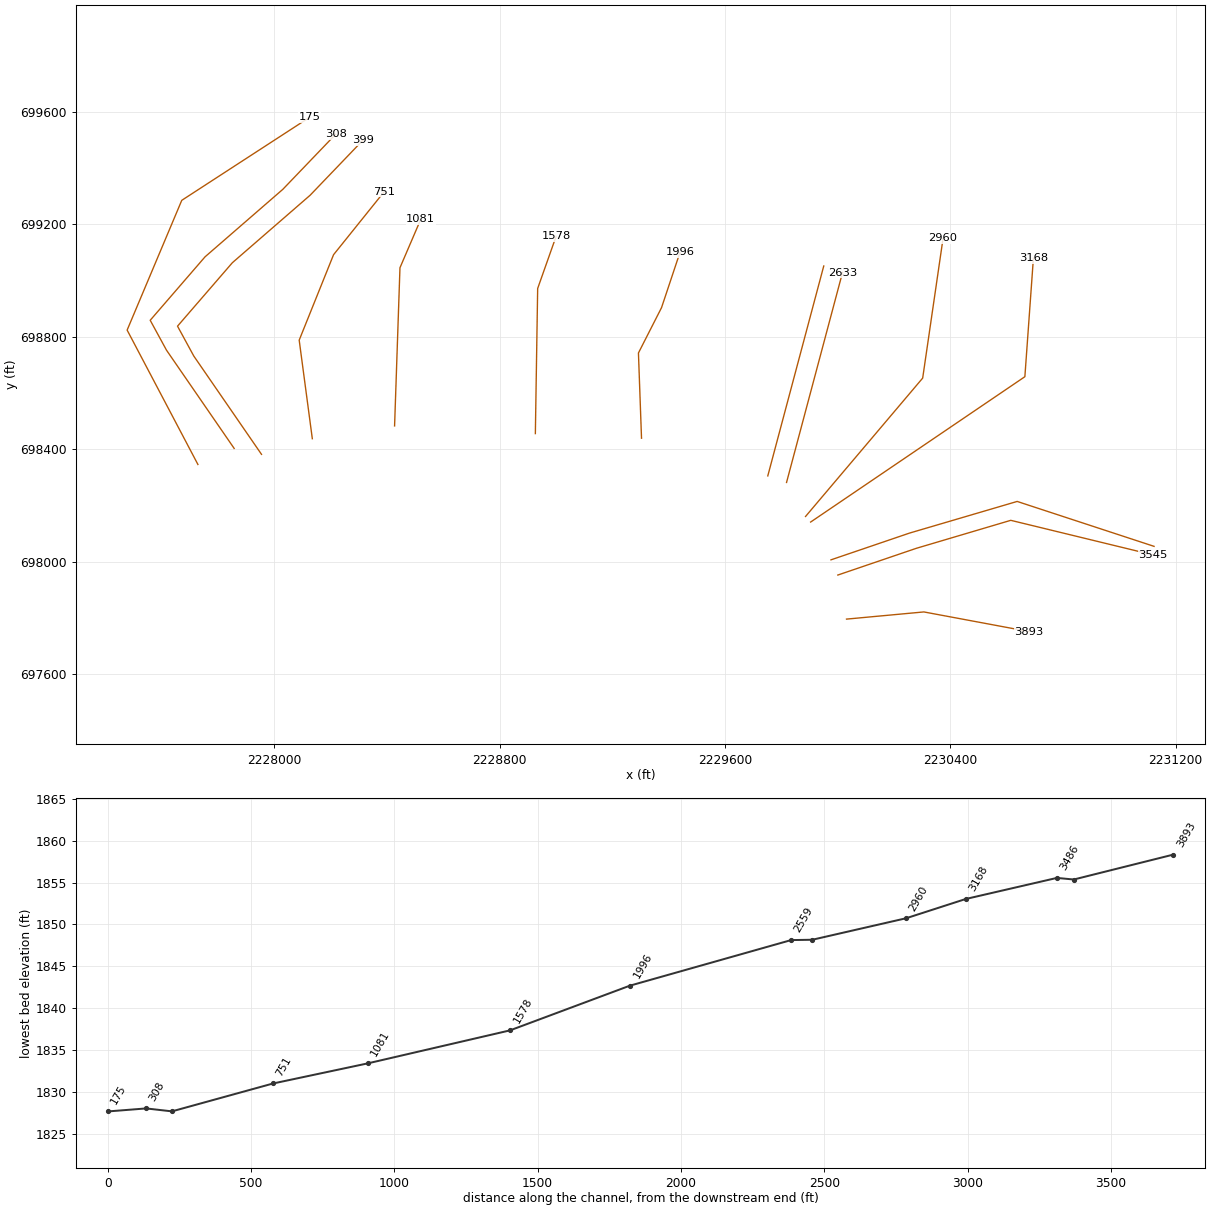
HEC-RAS study LAURELCK.prj: LAURELCK

--- LAURELCK.g01 (geometry) --- (continued)

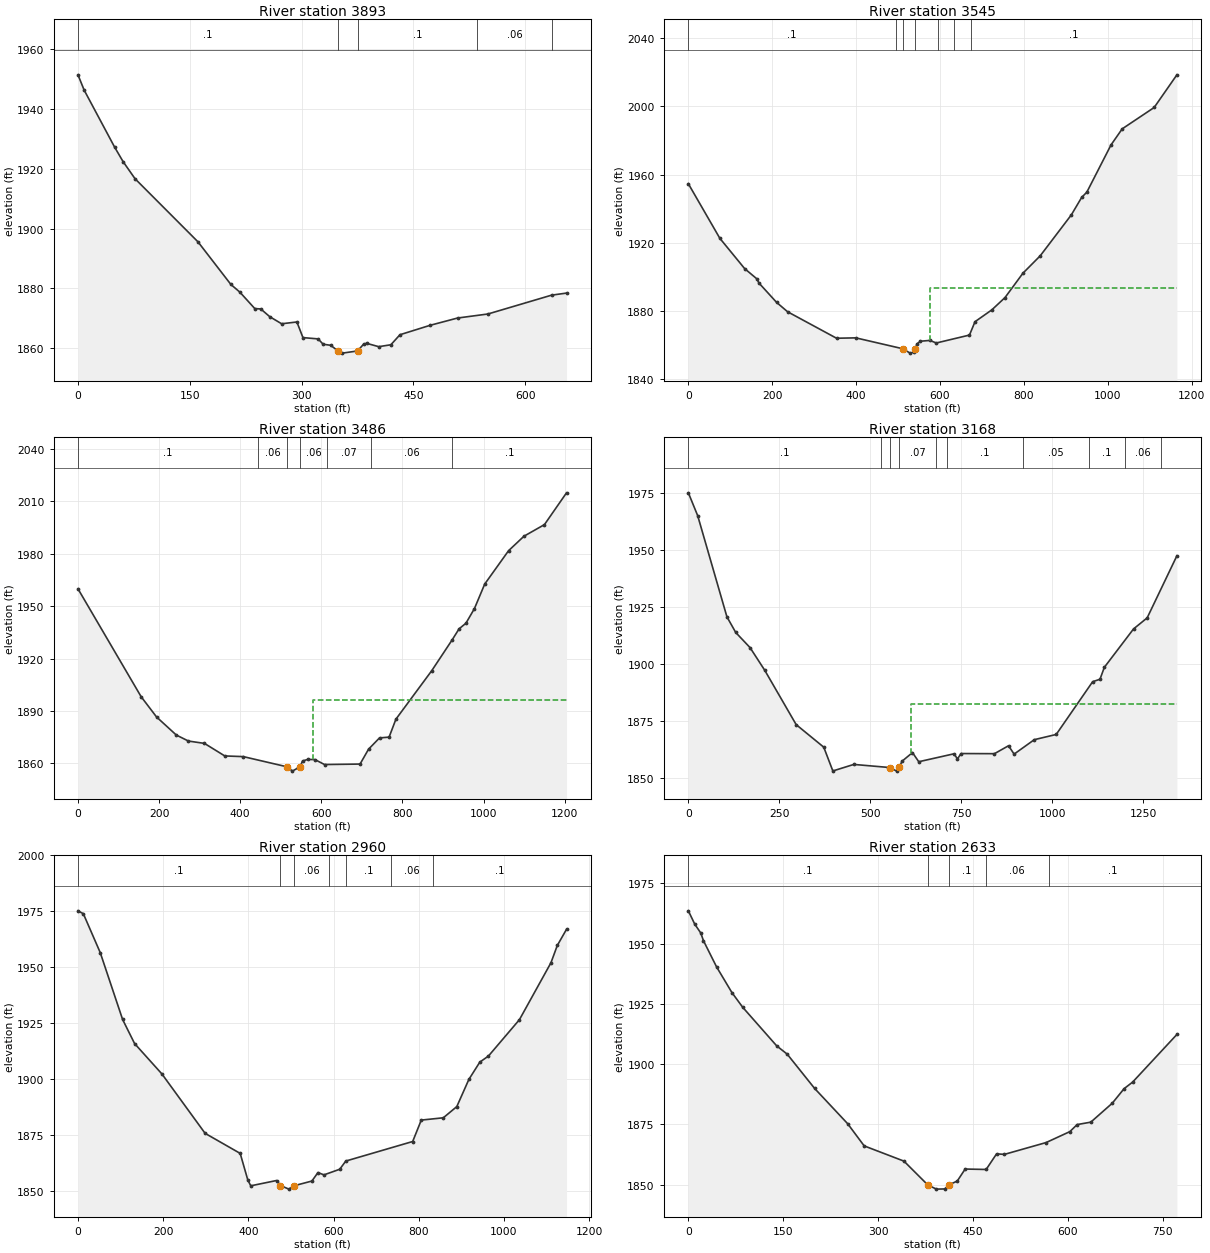
Type RM Length L Ch R = 1 ,3893    ,336.6,347.8,349.7
BEGIN DESCRIPTION:
Structure XS 4
END DESCRIPTION:
XS GIS Cut Line= 3
 2230031.9005168697796.0082754032230306.40049044697821.547830742
2230679.82299537697751.765992791
#Sta/Elev= 30
       0 1951.52     8.3  1946.4    49.1 1927.35    60.5 1922.48    76.6 1916.73
     161 1895.62   205.2 1881.34   217.2 1878.78   237.3 1873.26   245.3 1873.14
   257.4 1870.54   273.3 1868.18   293.8 1868.78   301.9 1863.55   322.3 1863.11
     329 1861.33   339.2 1860.97   349.5 1858.96   354.8 1858.35   375.2 1859.08
   383.3 1861.35   387.4 1861.63   403.6 1860.51   419.9 1861.15   432.1 1864.51
   472.8 1867.68   509.4  1870.1   550.1 1871.45   635.6 1877.76   655.6 1878.45
#Mann= 5 ,-1,0
       0      .1       0   349.5    .045       0   375.2      .1       0
  535.69     .06       0  635.69      .1       0
Bank Sta=349.5,375.2
XS Rating Curve= 0 ,0
Exp/Cntr(USF)=0,0
Exp/Cntr=0.3,0.1

Type RM Length L Ch R = 1 ,3545    ,58.9,58.9,58.7
BEGIN DESCRIPTION:
Structure XS 3
END DESCRIPTION:
XS GIS Cut Line= 4
2230001.06347115697952.7462710462230279.54763486698047.786165646
2230615.01116329698147.3935485222231120.70673707698024.239125572
#Sta/Elev= 30
       0 1954.66    75.1 1922.67   134.3 1904.89   163.5 1898.88   168.1 1896.52
   210.4 1885.11   236.6 1879.62   353.3  1864.1   399.2 1864.32   511.9  1857.9
   528.6 1855.37   536.9  1855.9   540.71857.954   545.3 1860.82   553.3 1862.35
   575.8 1862.81   591.2 1861.32   670.2 1865.96   683.4  1873.8   723.6 1880.75
     755 1887.97   797.7 1902.24   838.9 1912.43     913 1936.41   937.7 1946.67
     950 1949.74  1007.7 1977.46  1034.3 1986.85  1110.5 1999.37  1164.7 2018.52
#Mann= 7 ,-1,0
       0      .1       0  494.26     .06       0   511.9    .045       0
   540.7     .06       0  594.26      .1       0  634.26     .07       0
  674.19      .1       0
#XS Ineff= 2 , 0
                          577.04         1893.38
Permanent Ineff=
       F       F
Bank Sta=511.9,540.7
XS Rating Curve= 0 ,0
Exp/Cntr=0.3,0.1

Type RM Length L Ch R = 1 ,3486    ,311.5,318.3,320.7
BEGIN DESCRIPTION:
Structure XS 2
END DESCRIPTION:
XS GIS Cut Line= 4
2229976.72927338698006.850289202 2230255.2134371698101.890183802
2230637.70562164698214.5610822682231123.80592204698054.828815668
#Sta/Elev= 30
       0 1959.87   155.8 1898.13   193.8 1886.54   242.5 1876.21   272.4 1872.77
   311.9 1871.43     362 1864.25   407.8 1863.86   516.3 1857.99   528.8 1855.56
   547.31858.046   553.8 1861.33   566.3 1862.26   584.4 1862.16     608 1859.33
   695.6  1859.6   716.6 1868.13   743.6 1874.57   767.2 1875.01     784 1885.28
   872.4 1913.04     923 1930.77   939.8 1936.99   956.6 1940.16   977.7 1948.59
    1003  1962.6  1061.9 1981.71  1099.8 1989.97  1150.3 1996.62  1204.7  2014.8
#Mann= 7 ,-1,0
       0      .1       0  444.26     .06       0   516.3    .045       0
   547.3     .06       0  614.26     .07       0     723     .06       0
     923      .1       0
#XS Ineff= 2 , 0
                          579.21         1896.48
Permanent Ineff=
       F       F
Bank Sta=516.3,547.3
XS Rating Curve= 0 ,0
Exp/Cntr=0.3,0.1

Type RM Length L Ch R = 1 ,3168    ,202.1,207.8,206.8
BEGIN DESCRIPTION:
Structure XS 1
END DESCRIPTION:
XS GIS Cut Line= 3
2229904.47500447 698141.241602162230665.10631332698658.260346777
2230695.40486889699080.016773873
#Sta/Elev= 30
       0 1975.07    25.7 1965.03     106 1920.69   130.2 1913.84   169.6 1907.19
   209.9 1897.27   296.3 1873.43   372.1 1863.54   397.1 1853.11   454.7 1855.98
  553.481854.615   572.7 1853.04  579.681854.669   587.1 1857.36   615.9 1861.17
   633.2 1857.16     730 1860.64   739.6  1858.4   749.3 1860.75   841.2 1860.69
   879.9 1864.17   895.2  1860.5   950.7 1866.83  1010.9 1869.12  1111.1 1892.26
  1131.2 1893.32  1143.2 1898.56  1223.4 1915.39  1260.9 1920.24  1342.6 1947.47
#Mann= 10 ,-1,0
       0      .1       0     530     .06       0  553.48    .045       0
  579.68     .07       0     680     .05       0     710      .1       0
  919.71     .05       0 1099.71      .1       0 1199.71     .06       0
 1299.71      .1       0
#XS Ineff= 2 , 0
                          610.54         1882.48
Permanent Ineff=
       F       F
Bank Sta=553.48,579.68
XS Rating Curve= 0 ,0
Exp/Cntr(USF)=0,0
Exp/Cntr=0.3,0.1

Type RM Length L Ch R = 1 ,2960    ,318.8,327.3,334.3
BEGIN DESCRIPTION:
Structure XS 4
END DESCRIPTION:
XS GIS Cut Line= 3
     2229886.419      698161.1542230302.27749374698653.297033263
2230374.66330929699150.491908426
#Sta/Elev= 30
       0 1975.15    12.6 1973.86    52.3 1956.46   104.8 1926.57   132.9 1915.82
   197.1 1902.22   298.5 1875.67   380.8 1866.71   398.6 1854.88   405.6 1852.22
   466.1 1854.59   475.3 1852.34   495.1 1850.74     508 1852.29   549.1 1854.35
   563.3 1858.14   577.5 1857.12   614.4 1859.62   628.7 1863.29   785.7 1872.03
   805.9  1881.6   857.6 1882.63   889.3 1887.64   917.6 1899.79   943.3 1907.52
   963.5 1910.22  1036.3  1926.5  1110.3 1951.95  1125.2 1959.68  1146.8 1966.89
#Mann= 7 ,-1,0
       0      .1       0   475.3    .045       0     508     .06       0
     590     .07       0     630      .1       0  734.32     .06       0
  834.32      .1       0
Bank Sta=475.3,508
XS Rating Curve= 0 ,0
Exp/Cntr=0.3,0.1

Type RM Length L Ch R = 1 ,2633    ,74.4,74,72.5
BEGIN DESCRIPTION:
Structure XS 3
END DESCRIPTION:
XS GIS Cut Line= 2
2229818.93277501698282.1030060092230017.64421183699028.844062379
#Sta/Elev= 30
       0 1963.58    10.1 1958.06    19.7 1954.36    23.9 1951.19    44.6 1940.35
    68.9 1929.68      86 1923.57   139.8 1907.56   156.3 1904.16   199.7 1889.93
     252 1875.29   278.1  1866.1     341 1859.78  378.741849.898   392.3 1848.17
   405.6 1848.25   412.2 1849.95   425.3 1851.52   437.8  1856.5     471 1856.32
   487.5  1862.8   499.9 1862.58   565.8 1867.48   603.4 1872.02   614.9 1874.94
   636.5 1875.94   670.5  1883.8   689.2 1889.84   702.7 1892.56   772.7 1912.31
#Mann= 5 ,-1,0
       0      .1       0  378.74    .045       0   412.2      .1       0
     470     .06       0     570      .1       0
Bank Sta=378.74,412.2
XS Rating Curve= 0 ,0
Exp/Cntr(USF)=0,0
Exp/Cntr=0.3,0.1

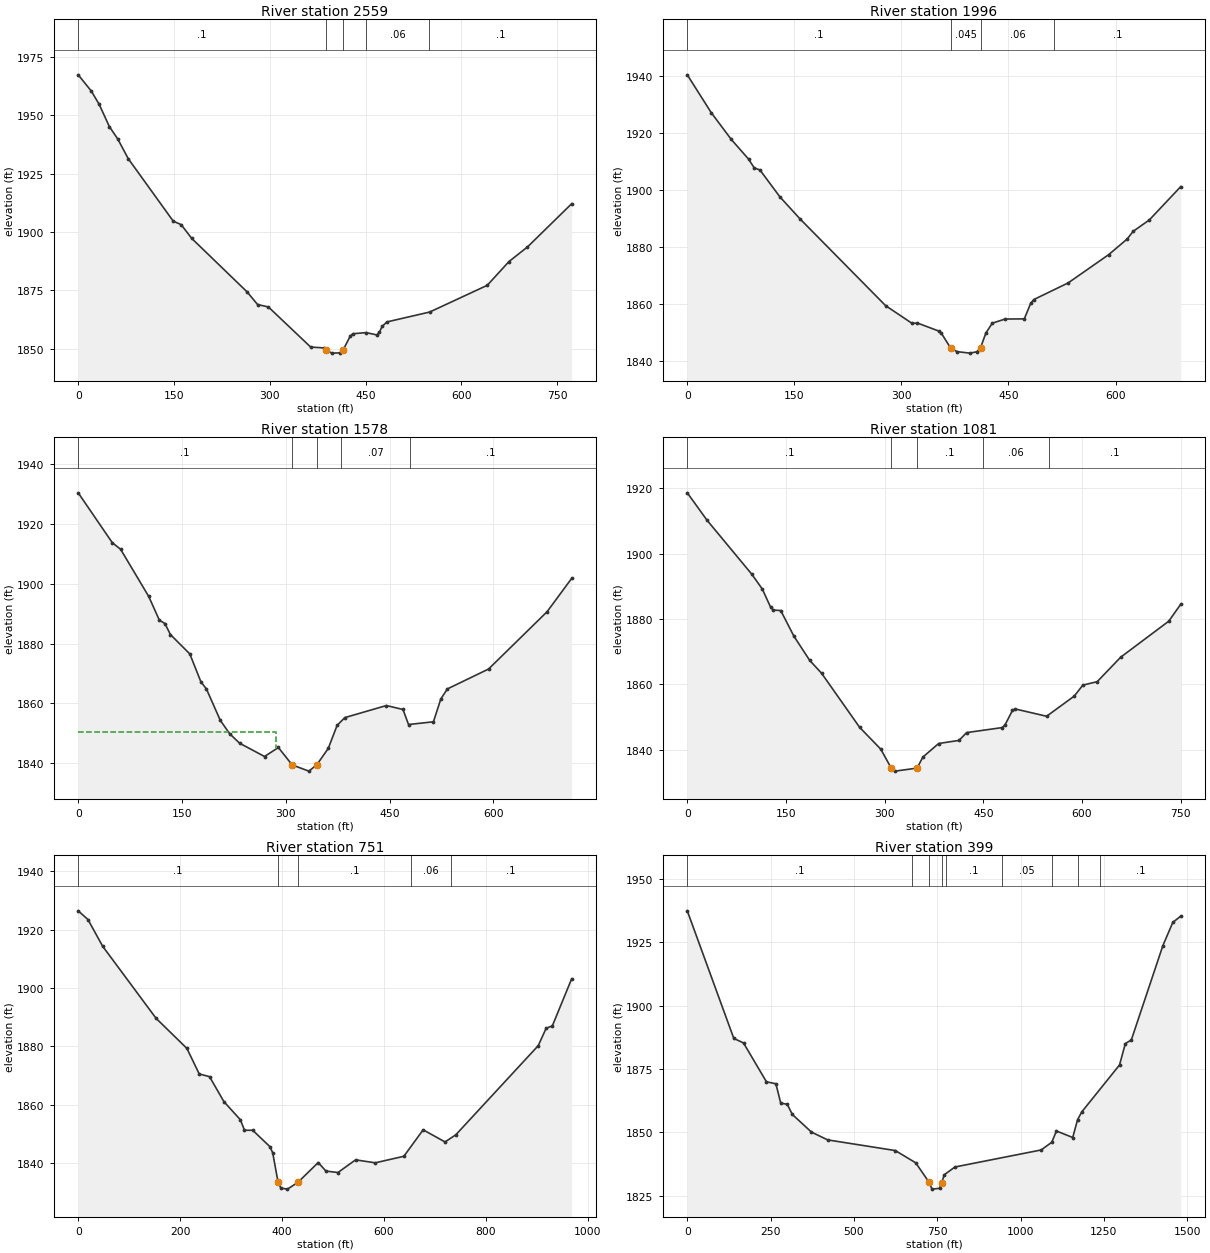
Type RM Length L Ch R = 1 ,2559    ,566.9,562.8,557.3
BEGIN DESCRIPTION:
Structure XS 2
END DESCRIPTION:
XS GIS Cut Line= 2
2229752.34897725698305.3840639472229951.06041407699052.125120318
#Sta/Elev= 30
       0  1967.3    20.5 1960.35    32.9 1954.62    48.7 1945.17    61.9 1939.83
    78.4 1931.37   148.8 1904.64   161.2 1903.15   177.8 1897.24   264.5 1874.34
   280.8 1868.95   297.8  1867.9     364 1850.73   384.7 1850.37  387.591849.525
   397.2 1848.13   409.6 1848.23   414.9 1849.55   426.1  1855.5   430.3 1856.44
     451 1856.91   467.5 1855.93   471.7 1857.08   475.8 1859.55   483.5  1861.5
   550.3 1865.72   640.5 1877.17   674.5 1887.34   703.5  1893.6   772.7 1912.11
#Mann= 5 ,-1,0
       0      .1       0  387.59    .045       0   414.9      .1       0
     450     .06       0     550      .1       0
Bank Sta=387.59,414.9
XS Rating Curve= 0 ,0
Exp/Cntr(USF)=0,0
Exp/Cntr=0.3,0.1

Type RM Length L Ch R = 1 ,1996    ,405.4,418,425.3
BEGIN DESCRIPTION:
Structure XS 1
END DESCRIPTION:
XS GIS Cut Line= 4
2229304.02932283698439.4816037712229293.10429648698742.651084985
 2229375.0419941698903.795223648 2229440.5921522 699100.44569795
#Sta/Elev= 30
       0 1940.34    33.7 1927.02    61.7 1917.65    85.8 1910.79    93.8 1907.68
   101.8 1906.96   129.8 1897.51   157.8 1889.83   277.9 1859.34   315.2 1853.08
   322.4 1853.25   352.2 1850.44   355.6 1849.82     369 1844.48     378  1843.2
     396 1842.68   405.7 1843.16  410.871844.547   418.4 1849.75   427.4  1853.2
   445.3 1854.64   472.2  1854.7   481.2 1860.18   485.6 1861.49   533.6 1867.31
   590.5 1877.25   616.3 1882.72   624.7 1885.41   647.4 1889.42   691.4 1901.11
#Mann= 4 ,-1,0
       0      .1       0     369    .045       0  410.87     .06       0
  514.15      .1       0
Bank Sta=369,410.87
XS Rating Curve= 0 ,0
Exp/Cntr(USF)=0,0
Exp/Cntr=0.3,0.1

Type RM Length L Ch R = 1 ,1578    ,496.6,497.2,496.1
XS GIS Cut Line= 3
2228927.11591375698455.8691432962228935.30968351698972.076638336
2229000.85984161699157.802086288
#Sta/Elev= 30
       0 1930.39    49.3  1913.7    61.3 1911.51   101.9 1895.74   117.3 1887.81
   125.3 1886.69   133.3 1882.99   161.3 1876.53   177.3 1867.21   185.3 1864.81
   205.3 1854.34   218.9 1849.84   233.3 1846.67   269.3 1842.23   289.3 1845.24
   309.2 1839.42   333.4 1837.34   344.9 1839.48   361.4 1844.94   374.2 1852.65
   385.4 1855.24   445.4 1859.27   469.4 1857.95   477.4 1852.92   513.4 1853.84
   524.1 1861.49   533.5 1864.82   593.1 1871.48   677.7 1890.65   713.2 1901.79
#Mann= 5 ,-1,0
       0      .1       0   309.2    .045       0   344.9      .1       0
     380     .07       0     480      .1       0
#XS Ineff= 2 , 0
          285.47 1850.57
Permanent Ineff=
       F       F
Bank Sta=309.2,344.9
XS Rating Curve= 0 ,0
Exp/Cntr(USF)=0,0
Exp/Cntr=0.3,0.1

Type RM Length L Ch R = 1 ,1081    ,338.3,329.9,324.9
BEGIN DESCRIPTION:
Structure XS 4
END DESCRIPTION:
XS GIS Cut Line= 3
2228427.29595823698483.1817091712228446.41475435699045.820566199
2228520.15868221699217.889731213
#Sta/Elev= 30
       0 1918.61      30 1910.23    98.1 1893.68   114.1 1889.14   126.6 1883.63
   130.5 1882.72   142.1 1882.56   162.1 1874.71   186.1 1867.31   204.1 1863.38
   262.1 1846.78   294.2 1840.11   310.2 1834.26     316 1833.39   349.31834.315
   358.2  1837.7   382.2 1841.85   413.1  1842.8   424.7 1845.19   478.3 1846.71
   482.8 1847.43   494.3 1851.96   498.3 1852.44   546.3 1850.19   588.4 1856.38
   601.4 1859.73   623.2 1860.78   658.8 1868.26     732 1879.31   750.2  1884.5
#Mann= 5 ,-1,0
       0      .1       0   310.2    .045       0   349.3      .1       0
     450     .06       0     550      .1       0
Bank Sta=310.2,349.3
XS Rating Curve= 0 ,0
Exp/Cntr(USF)=0,0
Exp/Cntr=0.3,0.1

Type RM Length L Ch R = 1 ,751     ,361.3,352.6,349.1
XS GIS Cut Line= 4
2228135.21970926698437.730439001 2228088.6274398698788.281799692
2228210.65481219699092.2408909232228390.36785153699316.327520225
#Sta/Elev= 30
       0 1926.43    19.1 1923.45    47.9  1914.3   152.8 1889.57   213.3 1879.25
   237.5 1870.48   257.7 1869.56   285.9    1861   318.2 1854.79   326.3 1851.18
   342.4 1851.18   376.2 1845.56   381.7 1843.43   392.1 1833.46   397.7 1831.35
   410.6 1830.99   430.9 1833.28     471 1840.11   486.2 1837.17   509.8 1836.69
   544.3 1841.03     583 1840.01   639.1 1842.26   676.9 1851.33   719.9 1847.17
   741.1 1849.64   902.9 1880.22   918.2 1886.13   930.5    1887   968.4 1903.14
#Mann= 5 ,-1,0
       0      .1       0   392.1    .045       0   430.9      .1       0
  653.63     .06       0  731.17      .1       0
Bank Sta=392.1,430.9
XS Rating Curve= 0 ,0
Exp/Cntr(USF)=0,0
Exp/Cntr=0.3,0.1

Type RM Length L Ch R = 1 ,399     ,88.2,90.2,88.7
BEGIN DESCRIPTION:
Structure XS 3
END DESCRIPTION:
XS GIS Cut Line= 6
2227954.78856859698382.1252154332227714.43798889698731.726058635
2227656.65205351698838.0324981032227851.33602307699063.688917363
2228127.37667236699303.6785006272228315.20518788699499.810036176
#Sta/Elev= 30
       0 1937.31   139.6 1887.04   168.7 1885.26   237.6 1869.93   265.9 1869.18
   280.4 1861.55   299.8 1861.11   315.3 1857.07   372.6 1850.13   421.2 1847.06
   624.1 1842.86   685.4 1838.03   725.8 1830.31   734.3 1827.66     757 1827.97
  763.121830.142   771.2 1833.33     803 1836.38  1061.7 1843.09  1093.5 1846.11
  1107.7 1850.56  1156.5    1848    1171    1855  1183.6 1858.08    1297 1876.59
  1314.3    1885  1332.3 1886.43  1427.1 1923.64  1456.8 1932.75  1480.6 1935.22
#Mann= 9 ,-1,0
       0      .1       0  675.25     .07       0   725.8    .045       0
  763.12     .07       0  775.25      .1       0  943.28     .05       0
 1093.28     .07       0 1173.28     .06       0 1239.06      .1       0
Bank Sta=725.8,763.12
XS Rating Curve= 0 ,0
Exp/Cntr(USF)=0,0
Exp/Cntr=0.3,0.1

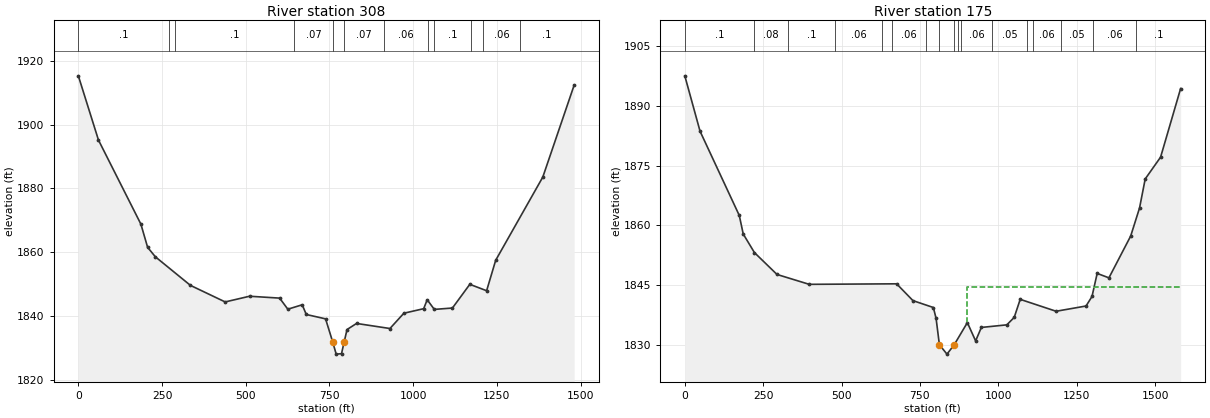
Type RM Length L Ch R = 1 ,308     ,128.3,133.8,140.2
BEGIN DESCRIPTION:
Structure XS 2
END DESCRIPTION:
XS GIS Cut Line= 6
2227857.80537417698403.0798865412227617.45479447698752.680729743
2227559.66885909 698858.987169212227754.35282865699084.643588471
2228030.39347794699324.6331717342228218.22199346699520.764707284
#Sta/Elev= 30
       0 1915.36    60.2 1895.18   186.8 1868.81   206.9 1861.53   229.9 1858.57
   334.7 1849.59   438.5 1844.39   511.3 1846.18   601.1 1845.59   625.6 1842.11
   668.5  1843.5   680.7 1840.45   738.3 1839.08   759.5 1831.86     770 1828.01
   785.9 1828.15  794.111831.967   802.4 1835.73   830.8 1837.64   930.5 1836.05
   972.1 1840.85  1031.2 1842.27  1041.8 1845.07    1063 1842.05  1117.1 1842.48
    1169 1849.92  1219.2 1847.91  1246.3 1857.47    1387 1883.59  1480.6 1912.44
#Mann= 12 ,-1,0
       0      .1       0     270     .08       0     290      .1       0
  645.25     .07       0   759.5    .045       0  794.11     .07       0
  913.28     .06       0 1043.28     .05       0 1063.28      .1       0
 1173.28     .07       0 1209.06     .06       0 1319.06      .1       0
Bank Sta=759.5,794.11
XS Rating Curve= 0 ,0
Exp/Cntr(USF)=0,0
Exp/Cntr=0.3,0.1

Type RM Length L Ch R = 1 ,175     ,,,
BEGIN DESCRIPTION:
Structure XS 1
END DESCRIPTION:
XS GIS Cut Line= 4
2227729.03451787698346.0612550252227477.75891182698824.031157841
2227671.67812953699285.6135211312228125.06672306699580.589232583
#Sta/Elev= 30
       0 1897.51    48.7 1883.59   173.8 1862.46   186.4  1857.8   222.1 1853.14
   294.1 1847.65   396.9 1845.17   675.7  1845.3   727.8 1841.08   792.9 1839.35
   801.6 1836.61  812.141829.994   836.3 1827.65   859.3 1829.99   901.3 1835.56
   927.7 1830.97     946 1834.35  1027.2    1835  1050.8 1836.87  1069.9  1841.4
  1184.4 1838.41  1279.9 1839.73  1298.9 1842.12  1315.4 1847.91  1352.9  1846.8
  1422.3 1857.29  1450.6 1864.35  1468.6 1871.62  1517.7  1877.1  1581.6 1894.32
#Mann= 17 ,-1,0
       0      .1       0     220     .08       0     330      .1       0
     480     .06       0     630      .1       0     660     .06       0
     770      .1       0  812.14    .045       0   859.3      .1       0
     870     .05       0     880     .06       0     980     .05       0
 1090.66     .08       0 1110.66     .06       0 1200.66     .05       0
 1300.66     .06       0 1440.66      .1       0
#XS Ineff= 2 , 0
                          900.12          1844.5
Permanent Ineff=
       F       F
Bank Sta=812.14,859.3
XS Rating Curve= 0 ,0
Exp/Cntr(USF)=0,0
Exp/Cntr=0.3,0.1
LCMann Table=0

Chan Stop Cuts=-1
Use User Specified Reach Order=0
Composite Channel Slope=5